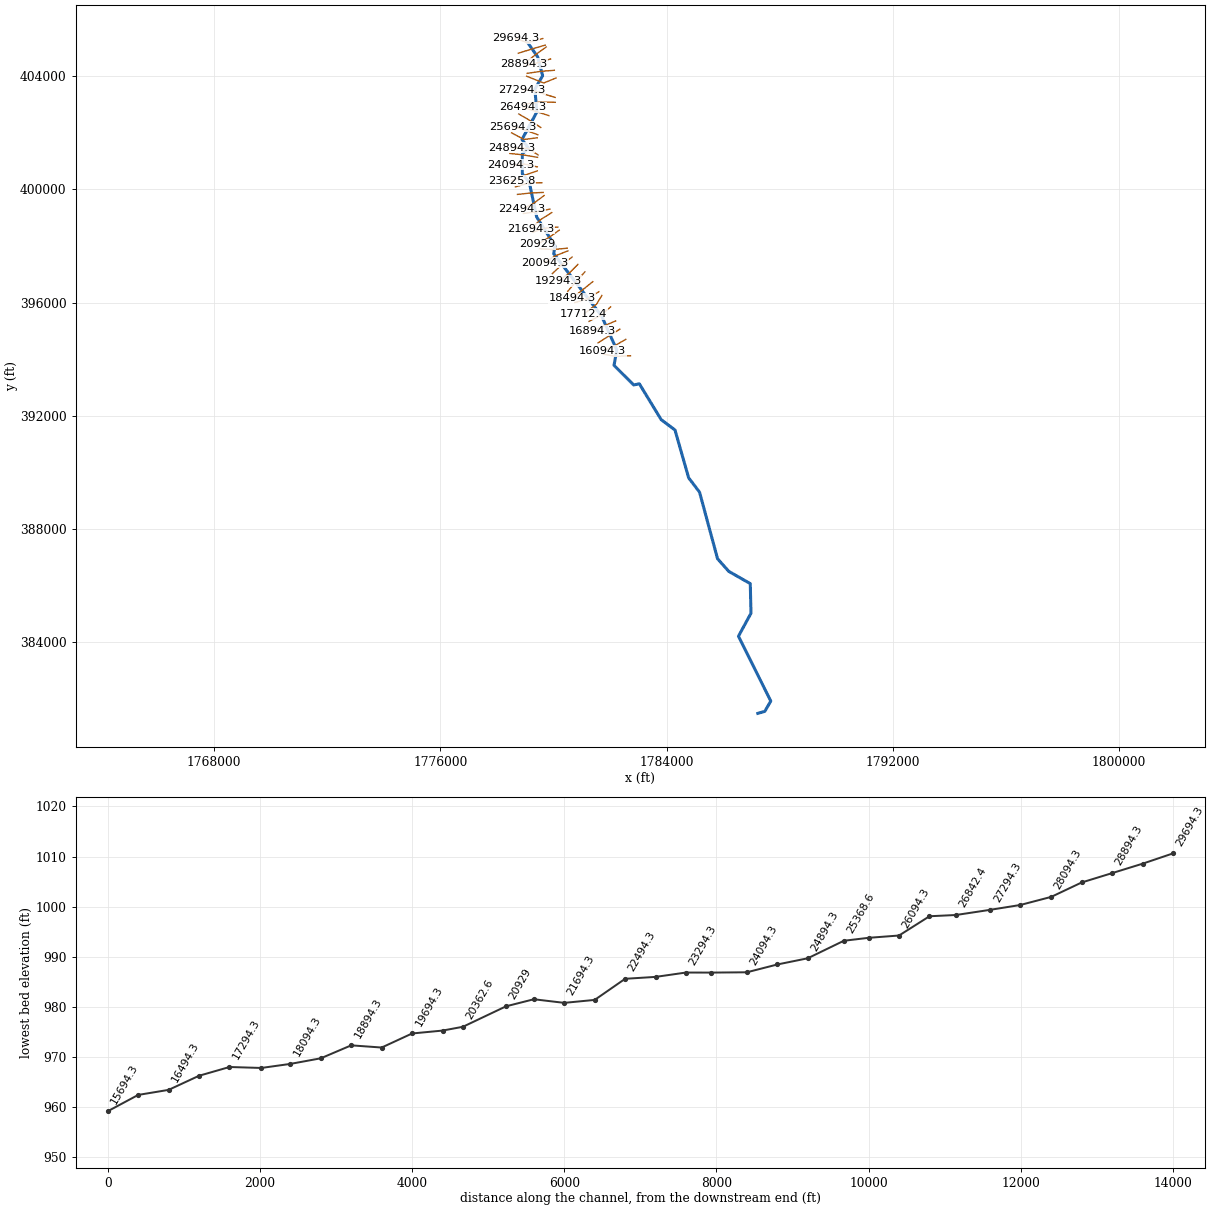
--- LtlPwPwCrk.prj (project) ---

Proj Title=LtlPwPwCrk
Current Plan=p01
Default Exp/Contr=0,0
English Units
Geom File=g01
Flow File=f01
Plan File=p01
BEGIN DESCRIPTION:
END DESCRIPTION:
DSS Export Rating Curves= 0
DSS Export Rating Curve Sorted= 0
DSS Export Volume Flow Curves= 0
DXF OffsetX= 0
DXF OffsetY= 0
DXF ScaleX= 0
DXF ScaleY= 0

--- LtlPwPwCrk.p01 (plan) ---

Plan Title=Floodplain
Program Version=4.00
Geom File=g01
Flow File=f01
K Sum by GR=0
Std Step Tol=0.01
Critical Tol=0.01
Num of Std Step Trials=20
Max Error Tol=0.3
Flow Tol Ratio=0.001
Split Flow NTrial=30
Split Flow Tol=0.02
Split Flow Ratio=0.02
Log Output Level=0
Friction Slope Method=1
Unsteady Friction Slope Method=2
Unsteady Bridges Friction Slope Method=1
Global Log Level=0
CheckData=False
Run HTab=0
Run UNet=0
Run PostProcess=0
UNET Theta=0
UNET Theta Warmup=0
UNET ZTol=0
UNET ZSATol=0
UNET MxIter=0
UNET MaxInSteps=0
UNET DtIC=0
UNET DtMin=0
UNET MaxCRTS=0
UNET WFStab=0
UNET SFStab=0
UNET WFX=0
UNET SFX=0
UNET DSS MLevel=0
UNET DZMax Abort=0
UNET Convert EG Bridges=0
UNET Use Existing IB Tables=0
UNET Froude Limit=0
UNET Froude Power=0
Write IC File=0
Echo Input=False
Echo Output=False
Write Detailed=0

--- LtlPwPwCrk.f01 (steady flow) ---

Flow Title=NFF Regression Equation
Program Version=4.00
Number of Profiles=1
Profile Names=P100yr
River Rch & RM=LtlPwPwCrk,Main      ,29694.3
1325.256
River Rch & RM=LtlPwPwCrk,Main      ,27687.5
1344.978
River Rch & RM=LtlPwPwCrk,Main      ,27294.3
1496.213
River Rch & RM=LtlPwPwCrk,Main      ,25368.6
1534.965
River Rch & RM=LtlPwPwCrk,Main      ,24894.3
1710.060
River Rch & RM=LtlPwPwCrk,Main      ,17712.4
1878.129
River Rch & RM=LtlPwPwCrk,Main      ,17294.3
2162.610
River Rch & RM=LtlPwPwCrk,Main      ,13694.3
2264.318
River Rch & RM=LtlPwPwCrk,Main      ,5249.7
2505.033
River Rch & RM=LtlPwPwCrk,Main      ,4894.3
2823.092
River Rch & RM=LtlPwPwCrk,Main      ,110.6
2970.764
Boundary for River Rch & Prof#=LtlPwPwCrk,Main      ,1
Up Type=0
Dn Type=3
Dn Slope=0.005032

--- LtlPwPwCrk.g01 (geometry) ---

Geom Title=USGS 3m DEM
Program Version=4.00

River Reach=LtlPwPwCrk     ,Main
Reach XY= 30
     1779077.753      405196.725     1779434.945      404689.497
     1779612.465      404021.922     1779337.779      403544.025
     1779407.374      402737.423     1778881.781      401764.910
     1779102.714      401475.471     1778894.557      401257.144
     1778894.790      400550.287     1779137.705      400261.538
     1779400.134      399030.153     1780047.696      398004.611
     1780005.279      397726.546     1781696.244      395530.376
     1782234.097      394326.548     1782137.015      393783.262
     1782830.218      393090.613     1783032.566      393130.958
     1783805.165      391863.652     1784293.429      391496.777
     1784776.128      389807.234     1785161.736      389301.292
     1785798.357      386947.283     1786195.475      386501.359
     1786955.741      386067.429     1786980.671      385021.754
     1786537.989      384209.637     1787680.478      381917.267
     1787468.170      381552.904     1787222.173      381482.229

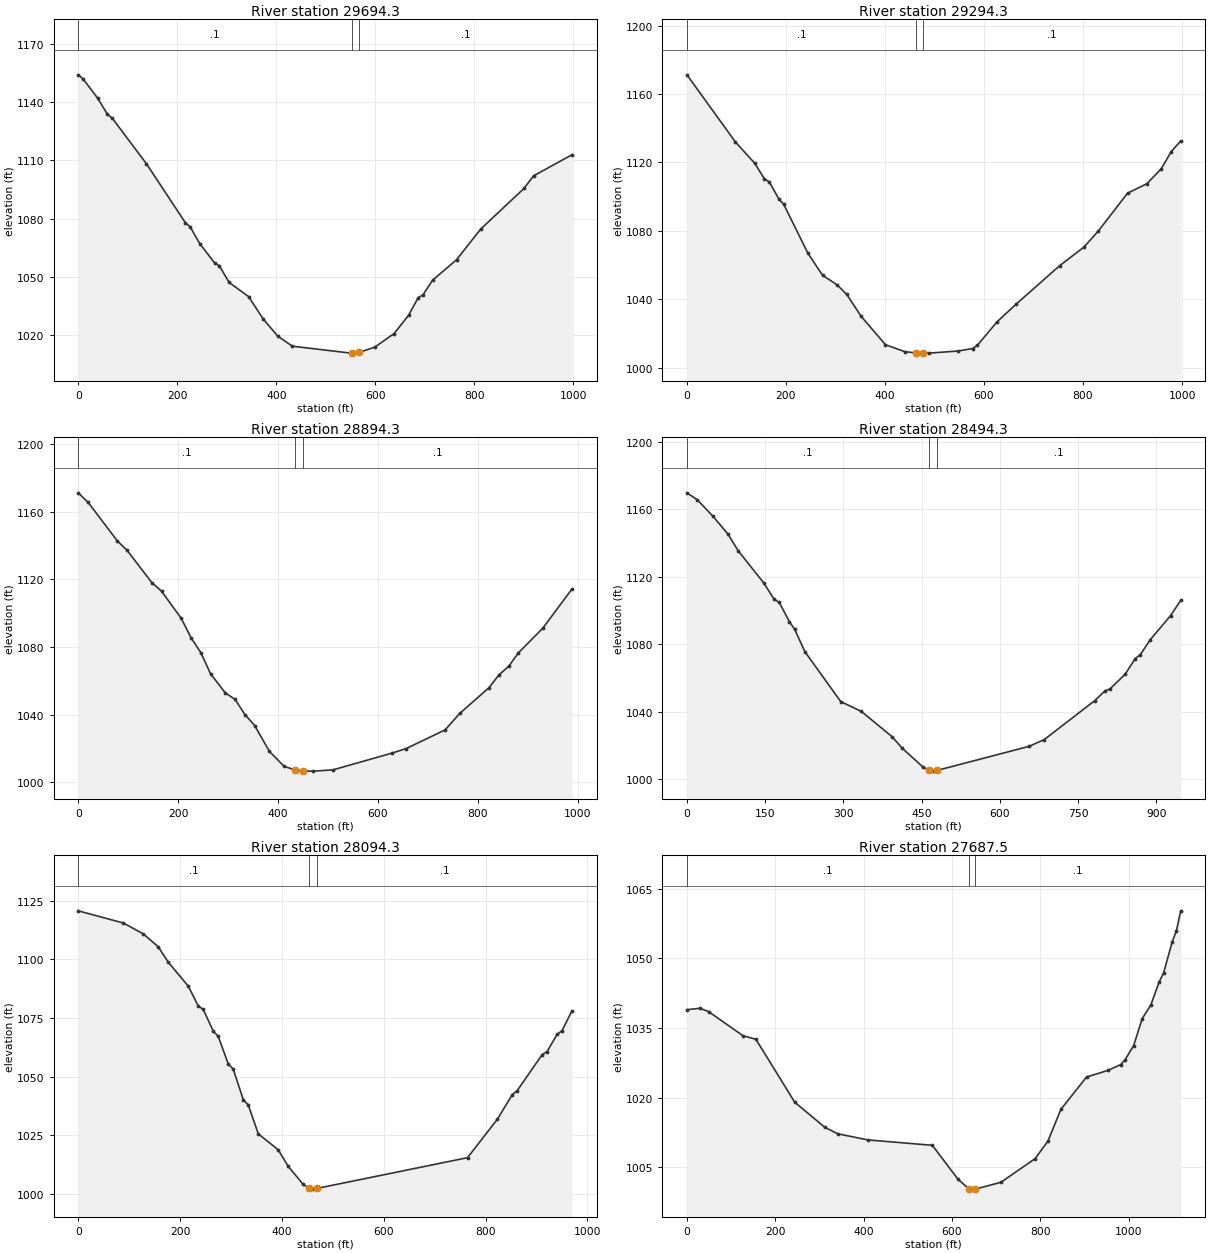
Type RM Length L Ch R = 1 ,29694.3,392.652,400,421.342
XS GIS Cut Line= 3
     1779614.741      405333.975     1779073.785      405187.577
     1778664.797      405341.509
#Sta/Elev= 30
       0 1154.06     9.8 1151.94    39.3 1142.02    59.0 1133.70    68.8 1131.68
   137.6 1108.29   216.3 1077.87   226.1 1075.69   245.8 1066.96   275.3 1057.17
   285.1 1055.62   304.8 1047.05   344.1 1039.76   373.6 1028.25   403.1 1019.36
   432.6 1014.19   550.6 1010.62   552.9 1010.64   567.9 1011.04   599.3 1013.77
   638.1 1020.71   667.2 1030.10   686.7 1039.21   696.4 1040.66   715.8 1048.19
   764.3 1058.80   812.9 1074.55   900.3 1095.48   919.7 1101.99   997.4 1112.87
#Mann= 3 , 0 , 0
       0     0.1       0   552.9   0.045       0   567.9     0.1       0
Bank Sta=   552.9,   567.9
Exp/Cntr=0.3,0.1

Type RM Length L Ch R = 1 ,29294.3,400.911,400,380.676
XS GIS Cut Line= 3
     1779706.243      405102.483     1779255.334      404971.717
     1778751.486      404814.433
#Sta/Elev= 30
       0 1171.18    97.8 1131.98   136.9 1119.49   156.5 1110.40   166.3 1108.59
   185.8 1098.54   195.6 1095.43   244.5 1066.85   273.9 1054.05   303.2 1048.48
   322.8 1042.86   352.1 1029.97   401.0 1013.47   440.1 1009.41     462 1008.71
     477 1008.58   489.0 1008.56   547.7 1009.80   577.0 1011.25   586.8 1013.20
   625.9 1026.73   665.0 1037.23   752.9 1059.69   801.8 1070.53   831.1 1079.99
   889.8 1102.00   928.9 1107.56   958.2 1116.33   977.8 1126.23   997.3 1132.52
#Mann= 3 , 0 , 0
       0     0.1       0     462   0.045       0     477     0.1       0
Bank Sta=     462,     477
Exp/Cntr=0.3,0.1

Type RM Length L Ch R = 1 ,28894.3,402.25,400,331.682
XS GIS Cut Line= 3
     1779740.599      405036.885     1779381.716      404779.713
     1778951.187      404442.520
#Sta/Elev= 30
       0 1171.19    19.6 1165.63    78.5 1142.69    98.1 1137.10   147.2 1118.17
   166.8 1113.03   206.0 1097.07   225.7 1085.59   245.3 1076.78   264.9 1064.24
   294.3 1052.95   314.0 1049.09   333.6 1040.15   353.2 1033.65   382.6 1018.39
   412.1 1009.49     434 1007.39     449 1006.78   470.8 1006.68   509.9 1007.43
   627.1 1017.25   656.4 1020.01   734.5 1031.09   763.8 1040.84   822.4 1056.03
   841.9 1063.53   861.4 1068.53   881.0 1076.56   929.8 1091.12   988.4 1114.36
#Mann= 3 , 0 , 0
       0     0.1       0     434   0.045       0     449     0.1       0
Bank Sta=     434,     449
Exp/Cntr=0.3,0.1

Type RM Length L Ch R = 1 ,28494.3,404.603,400,397.957
XS GIS Cut Line= 3
     1779893.759      404611.992     1779441.084      404479.435
     1778980.979      404362.063
#Sta/Elev= 30
       0 1169.81    19.7 1165.72    49.1 1156.19    78.6 1145.34    98.3 1135.42
   147.4 1116.31   167.1 1106.73   176.9 1104.84   196.5 1093.37   206.4 1088.95
   226.0 1075.67   294.8 1046.03   334.1 1040.26   393.1 1025.26   412.7 1018.40
   452.0 1007.36   464.2 1005.24   471.7 1004.81   479.2 1005.22   655.8 1019.49
   684.9 1023.52   781.8 1046.62   801.2 1052.38   810.9 1053.56   839.9 1062.22
   859.3 1071.55   869.0 1073.85   888.4 1082.85   927.1 1097.04   946.5 1106.06
#Mann= 3 , 0 , 0
       0     0.1       0   464.2   0.045       0   479.2     0.1       0
Bank Sta=   464.2,   479.2
Exp/Cntr=0.3,0.1

Type RM Length L Ch R = 1 ,28094.3,415.679,406.797,395.22
XS GIS Cut Line= 3
     1780026.761      404211.584     1779566.472      404176.876
     1779063.673      404103.764
#Sta/Elev= 30
       0 1120.78    88.4 1115.59   127.7 1110.95   157.1 1105.43   176.8 1098.84
   216.1 1088.63   235.7 1080.18   245.5 1078.65   265.2 1069.42   275.0 1067.15
   294.6 1055.41   304.5 1053.15   324.1 1040.16   333.9 1037.90   353.6 1025.55
   392.8 1018.71   412.5 1011.60   442.0 1003.92   454.1 1002.32   461.6 1001.93
   469.1 1002.25   764.5 1015.36   823.1 1031.77   852.4 1042.26   862.2 1044.04
   911.1 1059.37   920.8 1060.69   940.4 1068.02   950.1 1069.59   969.7 1078.09
#Mann= 3 , 0 , 0
       0     0.1       0   454.1   0.045       0   469.1     0.1       0
Bank Sta=   454.1,   469.1
Exp/Cntr=0.3,0.1

Type RM Length L Ch R = 1 ,27687.5,393.179,393.203,398.434
XS GIS Cut Line= 3
     1780084.013      403939.582     1779650.220      403762.994
     1779046.289      404002.158
#Sta/Elev= 30
       0 1038.96    29.3 1039.27    48.8 1038.56   126.8 1033.36   156.1 1032.59
   243.9 1019.05   312.2 1013.62   341.5 1012.23   409.8 1010.91   555.6 1009.75
   613.8 1002.42     638 1000.40   652.6 1000.31     653 1000.31   710.7 1001.78
   788.3 1006.88   817.4 1010.68   846.5 1017.48   904.6 1024.46   953.1 1025.88
   982.2 1027.15   991.9 1028.16  1011.3 1031.23  1030.7 1037.04  1050.1 1039.96
  1069.4 1045.01  1079.1 1046.88  1098.5 1053.53  1108.2 1055.99  1117.9 1060.26
#Mann= 3 , 0 , 0
       0     0.1       0     638   0.045       0     653     0.1       0
Bank Sta=     638,     653
Exp/Cntr=0.3,0.1

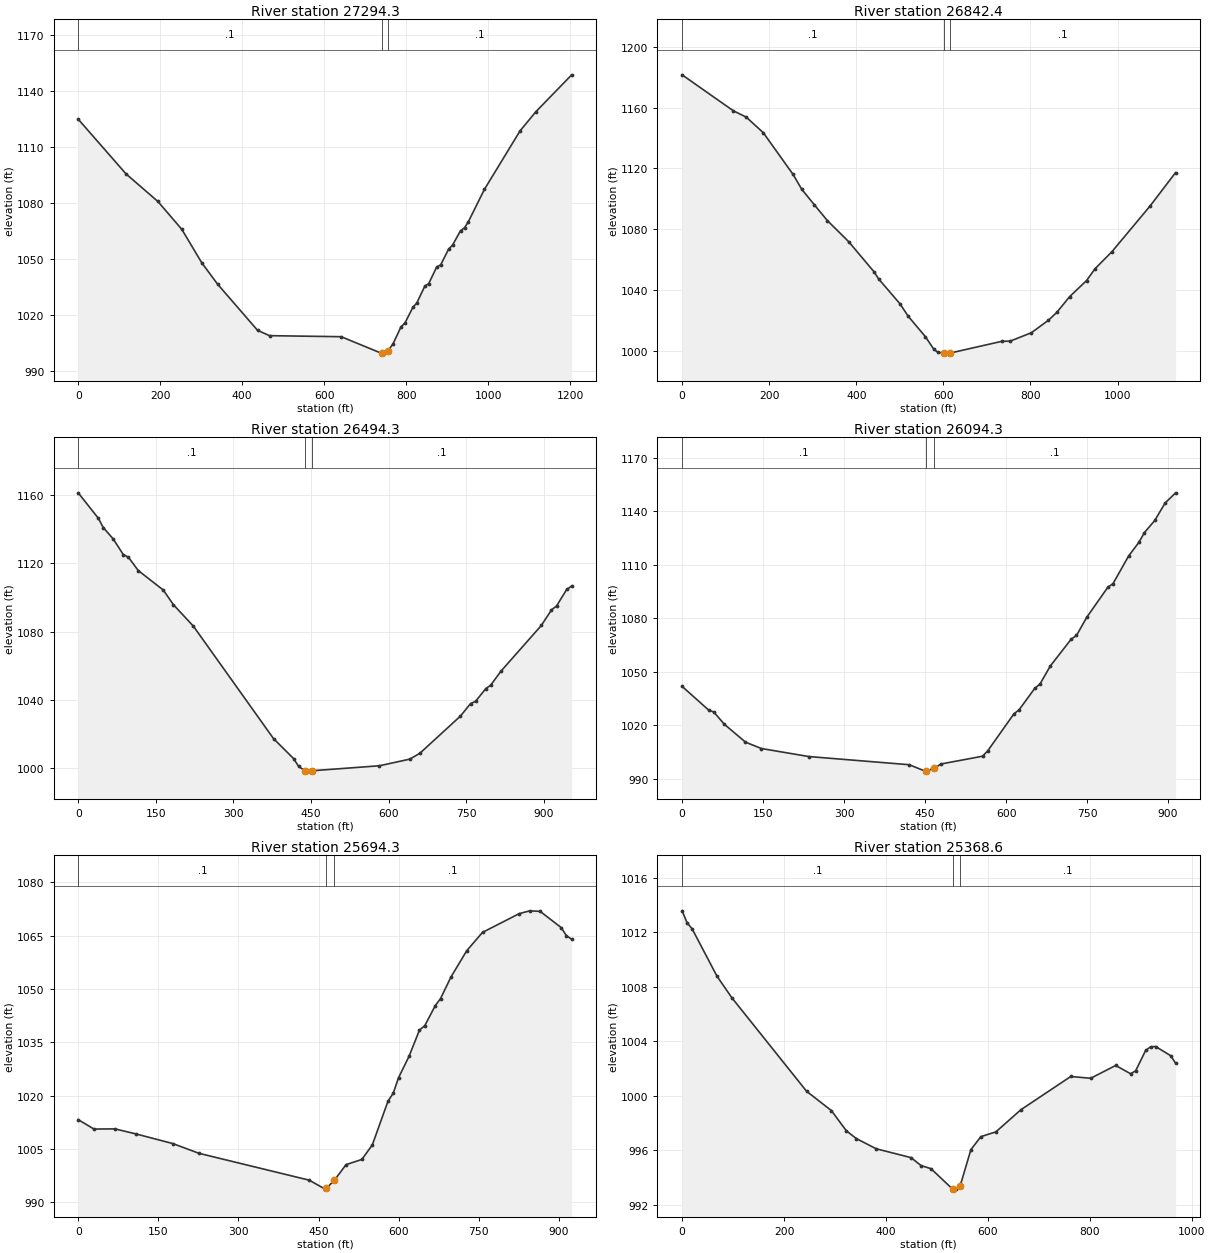
Type RM Length L Ch R = 1 ,27294.3,444.251,451.956,453.688
XS GIS Cut Line= 3
     1780050.908      403253.286     1779336.325      403476.355
     1778884.363      403531.844
#Sta/Elev= 30
       0 1124.86   116.7 1095.51   194.4 1080.73   252.8 1065.75   301.4 1047.82
   340.3 1036.28   437.5 1011.59   466.7 1008.72   641.6 1008.16   738.9  999.35
   741.1  999.38   756.1 1000.74   768.0 1004.31   787.3 1013.39   797.0 1015.47
   816.4 1023.91   826.1 1026.31   845.5 1035.27   855.2 1036.70   874.5 1045.56
   884.2 1046.71   903.6 1055.16   913.3 1057.33   932.7 1065.06   942.4 1066.59
   952.0 1069.94   990.8 1087.16  1078.0 1118.65  1116.8 1128.97  1203.9 1148.68
#Mann= 3 , 0 , 0
       0     0.1       0   741.1   0.045       0   756.1     0.1       0
Bank Sta=   741.1,   756.1
Exp/Cntr=0.3,0.1

Type RM Length L Ch R = 1 ,26842.4,355.906,348.044,341.903
XS GIS Cut Line= 3
     1780060.540      403079.912     1779531.215      403091.191
     1778933.014      403009.834
#Sta/Elev= 30
       0 1181.56   117.7 1157.87   147.1 1153.74   186.3 1143.49   254.9 1115.95
   274.5 1106.30   303.9 1095.89   333.4 1085.64   382.4 1071.73   441.2 1051.70
   451.0 1047.26   500.0 1030.90   519.6 1022.45   558.7 1009.13   578.1 1000.81
   587.9  998.74   600.7  998.38   607.3  998.31   615.7  998.37   733.9 1006.07
   753.4 1006.21   802.1 1011.75   841.0 1019.92   860.5 1025.15   889.7 1035.46
   928.7 1046.07   948.1 1053.85   987.1 1065.13  1074.7 1095.23  1133.2 1117.22
#Mann= 3 , 0 , 0
       0     0.1       0   600.7   0.045       0   615.7     0.1       0
Bank Sta=   600.7,   615.7
Exp/Cntr=0.3,0.1

Type RM Length L Ch R = 1 ,26494.3,405.822,400,395.399
XS GIS Cut Line= 3
     1779834.037      402608.947     1779409.741      402744.814
     1778926.394      402903.487
#Sta/Elev= 30
       0 1161.41    38.7 1146.56    48.4 1141.05    67.8 1134.29    87.2 1125.14
    96.9 1123.66   116.2 1115.77   164.6 1104.31   184.0 1095.78   222.8 1083.10
   377.7 1017.13   416.5 1005.40   426.1 1000.86     438  998.36   445.5  998.06
     453  998.30   582.5 1001.21   641.2 1005.11   660.7 1008.56   739.0 1030.36
   758.6 1037.70   768.4 1039.05   787.9 1046.44   797.7 1048.55   817.3 1056.70
   895.5 1083.57   915.1 1092.69   924.9 1095.01   944.5 1104.69   954.2 1106.72
#Mann= 3 , 0 , 0
       0     0.1       0     438   0.045       0     453     0.1       0
Bank Sta=     438,     453
Exp/Cntr=0.3,0.1

Type RM Length L Ch R = 1 ,26094.3,395.143,400,405.267
XS GIS Cut Line= 3
     1779546.067      402191.648     1779159.423      402440.600
     1778766.469      402668.266
#Sta/Elev= 30
       0 1041.77    48.9 1028.55    58.7 1027.37    78.3 1020.50   117.4 1010.47
   146.8 1006.90   234.8 1002.39   420.7  997.80   450.1  994.21   452.4  994.24
   467.4  995.81   479.2  998.20   556.5 1002.58   566.1 1005.63   614.5 1026.34
   624.1 1028.62   653.1 1040.66   662.8 1043.08   682.1 1053.27   720.7 1068.30
   730.4 1070.33   749.7 1080.66   788.4 1097.36   798.1 1099.44   827.0 1114.94
   846.4 1122.75   856.0 1127.98   875.4 1134.89   894.7 1144.72   914.0 1150.39
#Mann= 3 , 0 , 0
       0     0.1       0   452.4   0.045       0   467.4     0.1       0
Bank Sta=   452.4,   467.4
Exp/Cntr=0.3,0.1

Type RM Length L Ch R = 1 ,25694.3,328.269,325.698,321.061
XS GIS Cut Line= 3
     1779441.179      401933.620     1778998.918      402098.527
     1778563.265      402218.985
#Sta/Elev= 30
       0 1013.28    29.5 1010.63    68.8 1010.68   108.2 1009.26   177.0 1006.56
   226.2 1003.81   432.7  996.26   462.2  993.75   464.5  993.97   479.5  996.22
   501.5 1000.63   531.0 1002.09   550.6 1006.15   580.1 1018.50   589.9 1020.72
   599.7 1025.04   619.4 1031.07   639.0 1038.46   648.9 1039.69   668.5 1045.30
   678.4 1047.30   698.0 1053.38   727.5 1060.76   757.0 1065.90   825.7 1071.17
   845.4 1071.96   865.0 1071.80   904.4 1067.24   914.2 1064.95   924.0 1063.97
#Mann= 3 , 0 , 0
       0     0.1       0   464.5   0.045       0   479.5     0.1       0
Bank Sta=   464.5,   479.5
Exp/Cntr=0.3,0.1

Type RM Length L Ch R = 1 ,25368.6,477.536,474.302,438.797
XS GIS Cut Line= 3
     1779420.365      401826.362     1778955.384      401766.780
     1778513.913      402000.951
#Sta/Elev= 30
       0 1013.57     9.8 1012.69    19.5 1012.26    68.4 1008.78    97.7 1007.19
   244.2 1000.34   293.0  998.92   322.3  997.44   341.8  996.87   380.9  996.12
   449.3  995.47   468.8  994.89   488.4  994.66   530.7  993.17   537.4  993.16
   545.7  993.40   566.8  996.06   586.4  997.01   615.8  997.36   664.8  998.98
   762.7 1001.42   801.9 1001.29   850.9 1002.23   880.3 1001.62   890.1 1001.84
   909.7 1003.33   919.5 1003.60   929.3 1003.62   958.7 1002.95   968.5 1002.40
#Mann= 3 , 0 , 0
       0     0.1       0   530.7   0.045       0   545.7     0.1       0
Bank Sta=   530.7,   545.7
Exp/Cntr=0.3,0.1

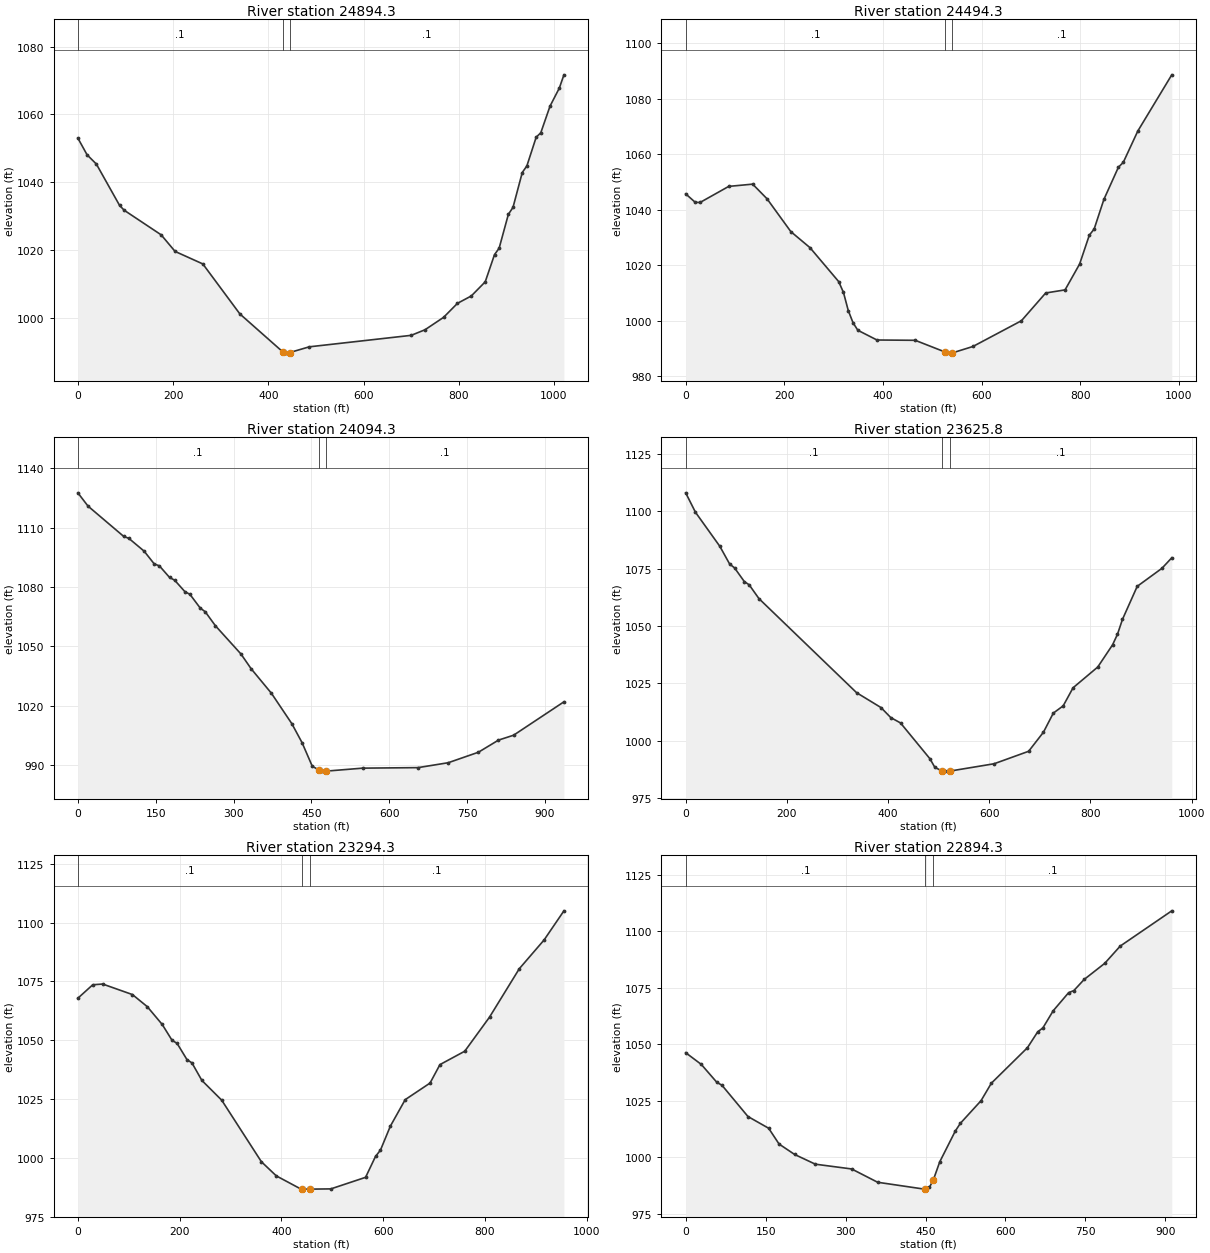
Type RM Length L Ch R = 1 ,24894.3,381.209,400,388.577
XS GIS Cut Line= 3
     1779455.485      401218.535     1779086.757      401454.152
     1778503.815      401474.686
#Sta/Elev= 30
       0 1053.02    19.4 1048.09    38.9 1045.37    87.5 1033.22    97.2 1031.77
   175.0 1024.51   204.2 1019.63   262.5 1015.94   340.3 1001.21   430.1  990.07
   437.6  989.66   445.1  989.84   486.2  991.52   700.1  994.90   729.2  996.55
   768.1 1000.20   797.3 1004.33   826.4 1006.51   855.6 1010.67   875.1 1018.69
   884.8 1020.57   904.2 1030.56   913.9 1032.59   933.4 1042.88   943.1 1044.83
   962.6 1053.28   972.3 1054.59   991.7 1062.44  1011.2 1067.75  1020.9 1071.66
#Mann= 3 , 0 , 0
       0     0.1       0   430.1   0.045       0   445.1     0.1       0
Bank Sta=   430.1,   445.1
Exp/Cntr=0.3,0.1

Type RM Length L Ch R = 1 ,24494.3,395.776,400,407.396
XS GIS Cut Line= 3
     1779431.527      401135.881     1778905.594      401224.603
     1778455.704      401272.432
#Sta/Elev= 30
       0 1045.81    19.4 1042.76    29.1 1042.70    87.3 1048.50   135.8 1049.31
   164.9 1044.05   213.3 1032.19   252.1 1026.42   310.3 1014.19   320.0 1010.28
   329.7 1003.77   339.4  999.36   349.1  996.66   387.9  993.15   465.5  993.04
   525.9  988.83   533.4  988.42   540.9  988.51   582.5  990.81   680.9 1000.09
   730.1 1010.09   769.4 1011.21   798.9 1020.52   818.6 1030.93   828.4 1033.14
   848.1 1043.79   877.6 1055.42   887.4 1057.14   916.9 1068.44   985.8 1088.70
#Mann= 3 , 0 , 0
       0     0.1       0   525.9   0.045       0   540.9     0.1       0
Bank Sta=   525.9,   540.9
Exp/Cntr=0.3,0.1

Type RM Length L Ch R = 1 ,24094.3,454.917,468.568,473.645
XS GIS Cut Line= 3
     1779424.369      400797.732     1778963.862      400898.159
     1778499.530      400867.376
#Sta/Elev= 30
       0 1127.67    19.6 1120.95    88.4 1105.61    98.2 1104.65   127.7 1098.17
   147.3 1091.67   157.1 1090.73   176.7 1084.87   186.6 1083.45   206.2 1077.69
   216.0 1076.31   235.7 1069.41   245.5 1067.49   265.1 1060.41   314.2 1046.16
   333.9 1038.68   373.1 1026.23   412.4 1010.85   432.1 1001.25   451.7  989.36
   463.8  987.53   471.3  986.86   478.8  986.87   548.9  988.37   655.5  988.63
   713.7  991.11   771.9  996.42   810.6 1002.56   839.7 1005.03   936.7 1021.93
#Mann= 3 , 0 , 0
       0     0.1       0   463.8   0.045       0   478.8     0.1       0
Bank Sta=   463.8,   478.8
Exp/Cntr=0.3,0.1

Type RM Length L Ch R = 1 ,23625.8,340.31,331.432,331.767
XS GIS Cut Line= 3
     1779419.491      400656.851     1778982.256      400503.790
     1778523.363      400311.743
#Sta/Elev= 30
       0 1107.98    19.3 1099.53    67.6 1084.65    86.9 1076.97    96.5 1075.32
   115.8 1069.36   125.5 1067.92   144.8 1061.92   337.8 1020.95   386.0 1014.48
   405.3 1010.12   424.6 1007.78   482.8  992.17   492.5  988.42   506.9  986.86
   512.0  986.80   521.9  986.81   609.6  990.01   677.8  995.44   707.1 1003.76
   726.6 1012.07   746.1 1015.23   765.6 1023.09   814.4 1032.13   843.7 1041.80
   853.4 1046.39   863.2 1052.85   892.4 1067.26   941.2 1075.10   960.7 1079.70
#Mann= 3 , 0 , 0
       0     0.1       0   506.9   0.045       0   521.9     0.1       0
Bank Sta=   506.9,   521.9
Exp/Cntr=0.3,0.1

Type RM Length L Ch R = 1 ,23294.3,399.165,400,393.014
XS GIS Cut Line= 3
     1779584.073      400237.299     1779135.481      400235.918
     1778650.058      400090.083
#Sta/Elev= 30
       0 1067.87    29.3 1073.59    48.8 1073.90   107.3 1069.43   136.5 1064.29
   165.8 1056.75   185.3 1049.97   195.0 1048.74   214.5 1041.81   224.3 1040.41
   243.8 1032.97   282.8 1024.58   360.8  998.44   390.1  992.44   438.8  986.81
   441.1  986.81   456.1  986.81   497.3  986.91   565.6  991.82   585.1 1000.69
   594.8 1003.35   614.3 1013.55   643.5 1024.81   692.3 1031.85   711.8 1039.69
   760.5 1045.37   809.2 1059.84   867.7 1080.39   916.5 1092.62   955.5 1104.99
#Mann= 3 , 0 , 0
       0     0.1       0   441.1   0.045       0   456.1     0.1       0
Bank Sta=   441.1,   456.1
Exp/Cntr=0.3,0.1

Type RM Length L Ch R = 1 ,22894.3,386.551,400,407.559
XS GIS Cut Line= 3
     1779632.079      399895.185     1779175.176      399873.954
     1778723.256      399824.877
#Sta/Elev= 30
       0 1046.28    29.2 1041.12    58.4 1033.19    68.1 1031.88   116.8 1018.06
   155.7 1012.86   175.2 1005.88   204.4 1001.27   243.3  996.97   311.4  994.86
   360.1  988.98   447.7  985.94   449.9  986.12   457.4  986.76   464.9  990.18
   476.7  998.03   505.8 1011.61   515.4 1015.06   554.1 1025.04   573.5 1032.79
   641.2 1048.49   660.5 1055.53   670.2 1057.25   689.5 1064.82   718.5 1072.84
   728.2 1073.74   747.6 1078.67   786.2 1085.80   815.3 1093.44   912.0 1109.03
#Mann= 3 , 0 , 0
       0     0.1       0   449.9   0.045       0   464.9     0.1       0
Bank Sta=   449.9,   464.9
Exp/Cntr=0.3,0.1

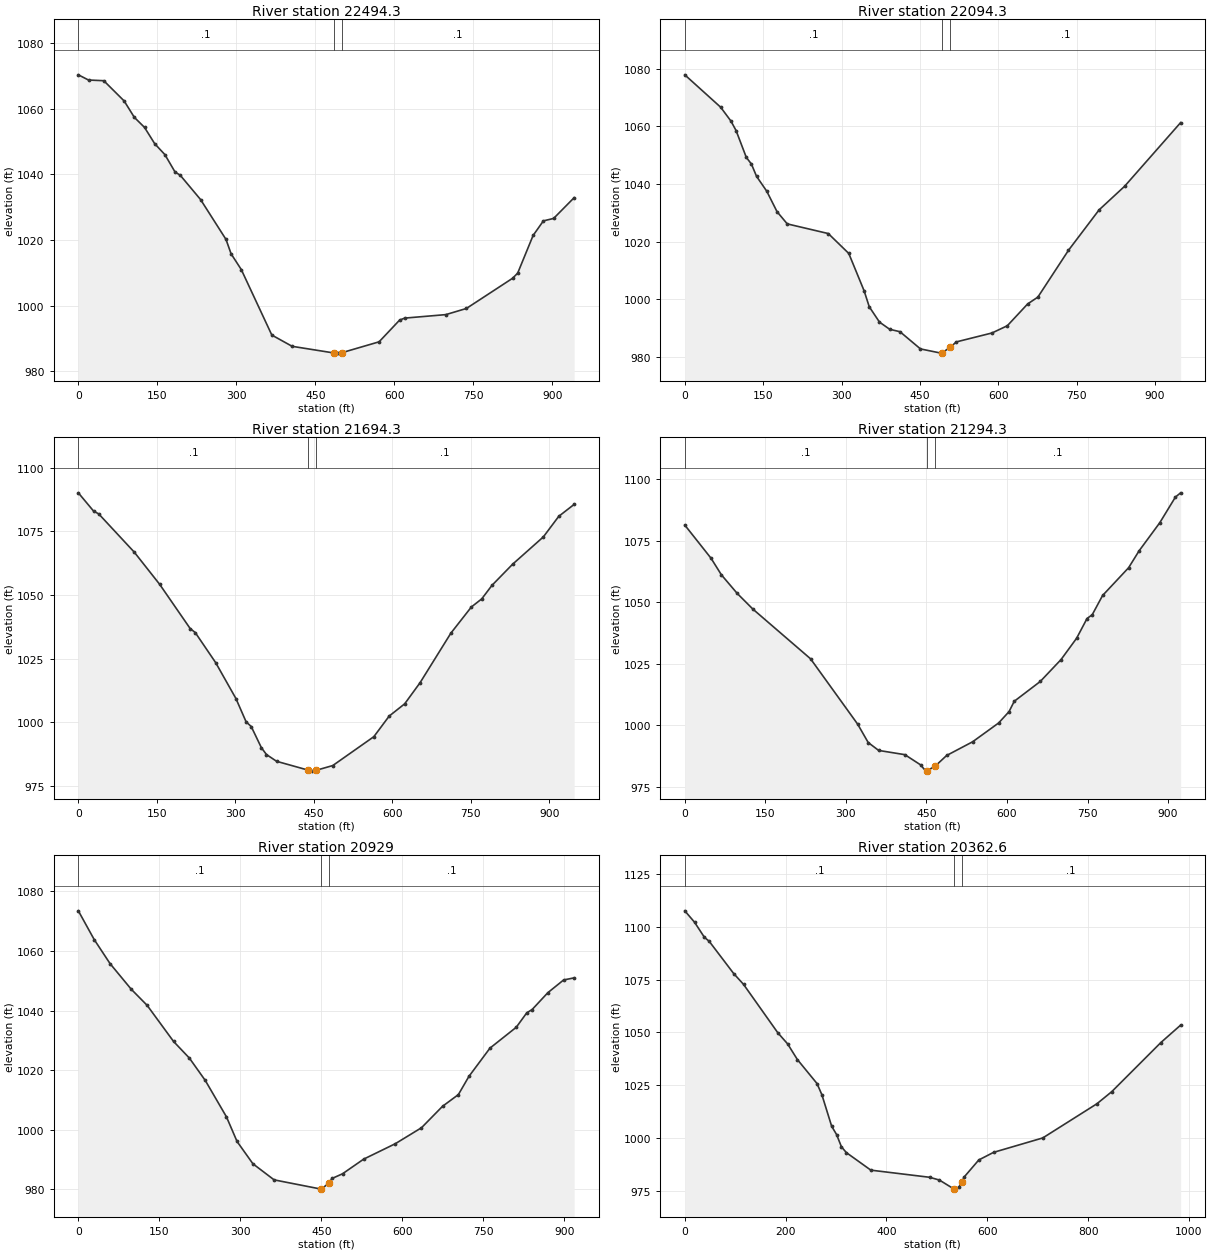
Type RM Length L Ch R = 1 ,22494.3,411.135,400,390.806
XS GIS Cut Line= 3
     1779664.982      399784.526     1779268.296      399491.904
     1778862.504      399301.377
#Sta/Elev= 30
       0 1070.26    19.3 1068.68    48.3 1068.47    87.0 1062.30   106.3 1057.32
   125.7 1054.25   145.0 1049.29   164.3 1045.98   183.6 1040.68   193.3 1039.72
   232.0 1032.31   280.3 1020.17   290.0 1015.78   309.3 1011.00   367.3  991.06
   405.9  987.63   485.4  985.60   492.9  985.56   500.4  985.70   570.9  989.00
   609.9  995.62   619.6  996.22   697.6  997.28   736.6  999.15   824.3 1008.34
   834.0 1009.91   863.3 1021.38   882.8 1025.81   902.2 1026.55   941.2 1032.88
#Mann= 3 , 0 , 0
       0     0.1       0   485.4   0.045       0   500.4     0.1       0
Bank Sta=   485.4,   500.4
Exp/Cntr=0.3,0.1

Type RM Length L Ch R = 1 ,22094.3,392.754,400,411.569
XS GIS Cut Line= 3
     1779867.789      399304.880     1779377.250      399207.684
     1778931.987      399151.108
#Sta/Elev= 30
       0 1077.86    68.6 1066.63    88.2 1061.85    98.1 1058.55   117.7 1049.23
   127.5 1046.92   137.3 1042.66   156.9 1037.48   176.5 1030.40   196.1 1026.16
   274.6 1022.81   313.8 1015.92   343.2 1002.94   353.0  997.42   372.6  992.10
   392.2  989.60   411.8  988.77   451.0  982.80   490.3  981.34   492.6  981.47
   507.6  983.32   519.6  985.23   587.9  988.33   617.2  990.83   656.2  998.41
   675.7 1000.77   734.3 1017.01   792.8 1031.01   841.6 1039.19   948.9 1061.29
#Mann= 3 , 0 , 0
       0     0.1       0   492.6   0.045       0   507.6     0.1       0
Bank Sta=   492.6,   507.6
Exp/Cntr=0.3,0.1

Type RM Length L Ch R = 1 ,21694.3,410.815,400,388.987
XS GIS Cut Line= 3
     1779933.519      399181.425     1779555.511      398943.160
     1779185.569      398606.081
#Sta/Elev= 30
       0 1090.13    29.1 1082.96    38.9 1081.86   106.9 1066.81   155.4 1054.16
   213.7 1036.78   223.4 1035.21   262.3 1023.42   301.1 1009.28   320.6 1000.10
   330.3  998.29   349.7  989.97   359.4  987.28   378.8  984.61   439.3  981.13
   446.8  980.75   454.3  981.07   486.1  982.94   564.6  994.29   594.0 1002.41
   623.5 1007.20   652.9 1015.50   711.8 1034.99   751.0 1045.28   770.7 1048.44
   790.3 1053.77   829.6 1062.05   888.4 1072.80   917.9 1080.90   947.3 1085.59
#Mann= 3 , 0 , 0
       0     0.1       0   439.3   0.045       0   454.3     0.1       0
Bank Sta=   439.3,   454.3
Exp/Cntr=0.3,0.1

Type RM Length L Ch R = 1 ,21294.3,354.905,365.284,370.863
XS GIS Cut Line= 3
     1780150.018      398672.383     1779693.623      398628.006
     1779250.829      398486.924
#Sta/Elev= 30
       0 1081.32    48.8 1067.88    68.3 1061.09    97.6 1053.59   126.8 1047.22
   234.2 1027.05   322.0 1000.50   341.5  993.08   361.0  989.87   409.8  988.15
   439.0  984.02   448.8  981.47     451  981.62     466  983.45   487.6  987.82
   536.0  993.38   584.4 1001.01   603.8 1005.62   613.5 1009.82   661.9 1017.85
   700.6 1026.74   729.6 1035.39   749.0 1043.40   758.7 1044.94   778.0 1052.75
   826.5 1064.03   845.8 1070.82   884.5 1082.28   913.6 1092.68   923.3 1094.41
#Mann= 3 , 0 , 0
       0     0.1       0     451   0.045       0     466     0.1       0
Bank Sta=     451,     466
Exp/Cntr=0.3,0.1

Type RM Length L Ch R = 1 ,20929,581.795,566.481,551.155
XS GIS Cut Line= 3
     1780199.228      398559.911     1779903.586      398350.181
     1779431.519      398057.079
#Sta/Elev= 30
       0 1073.46    29.4 1063.81    58.8 1055.73    98.0 1047.14   127.4 1041.74
   176.3 1029.63   205.7 1024.02   235.1 1016.52   274.3 1004.31   293.9  996.05
   323.3  988.56   362.5  983.17   448.9  980.09   450.2  980.06   463.9  982.13
   469.7  983.63   489.2  985.21   528.2  990.11   586.7  995.28   635.4 1000.66
   674.4 1007.86   703.7 1011.78   723.2 1017.88   762.2 1027.38   810.9 1034.38
   830.4 1039.24   840.1 1040.30   869.4 1045.99   898.6 1050.26   918.1 1050.96
#Mann= 3 , 0 , 0
       0     0.1       0   448.9   0.045       0   463.9     0.1       0
Bank Sta=   448.9,   463.9
Exp/Cntr=0.3,0.1

Type RM Length L Ch R = 1 ,20362.6,258.573,268.235,282.156
XS GIS Cut Line= 3
     1780482.904      397923.605     1779999.557      397878.000
     1779502.281      397905.011
#Sta/Elev= 30
       0 1107.47    19.4 1102.06    38.8 1094.99    48.5 1093.04    97.1 1077.80
   116.5 1072.73   184.5 1049.85   203.9 1044.61   223.3 1037.20   262.2 1025.88
   271.9 1020.59   291.3 1005.69   301.0 1001.78   310.7  995.98   320.4  993.24
   369.0  984.94   485.5  981.57   505.0  980.26   534.3  975.97   534.5  975.99
   544.1  976.96   549.5  979.55   553.8  981.60   583.1  989.74   612.4  993.34
   710.1 1000.16   817.5 1016.31   846.8 1022.00   944.4 1045.25   983.5 1053.46
#Mann= 3 , 0 , 0
       0     0.1       0   534.5   0.045       0   549.5     0.1       0
Bank Sta=   534.5,   549.5
Exp/Cntr=0.3,0.1

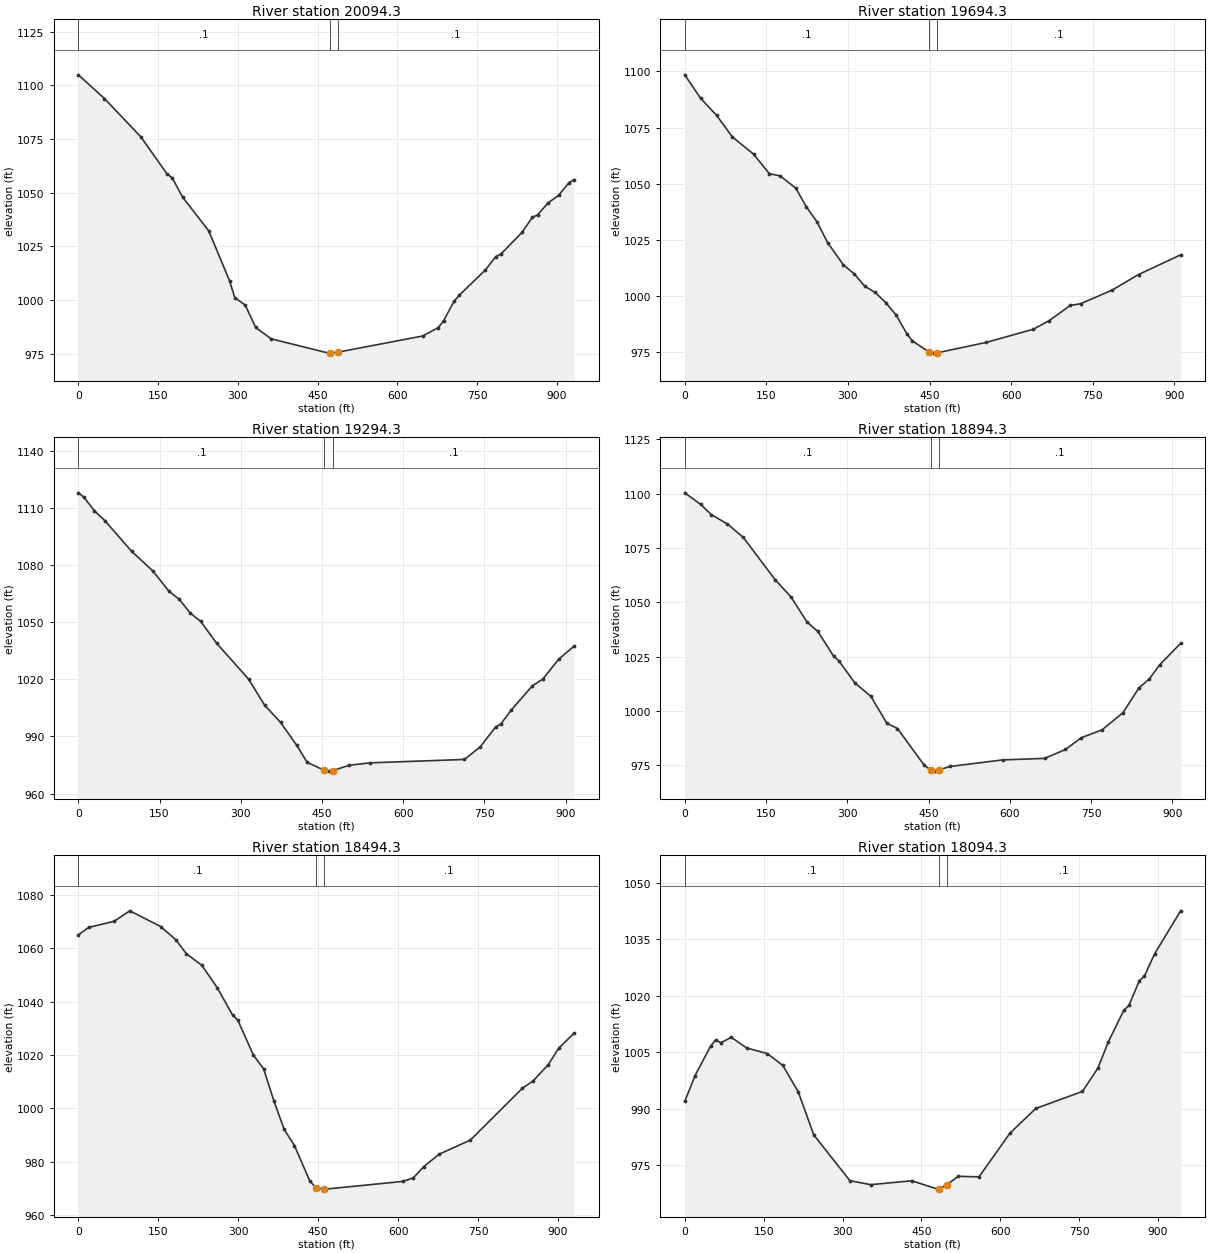
Type RM Length L Ch R = 1 ,20094.3,393.923,400,404.297
XS GIS Cut Line= 3
     1780507.357      397830.110     1780060.163      397653.714
     1779676.015      397415.502
#Sta/Elev= 30
       0 1104.86    49.1 1093.83   117.7 1075.93   166.8 1058.69   176.6 1056.88
   196.2 1047.87   245.3 1032.17   284.5 1008.89   294.3 1001.08   313.9  997.58
   333.6  987.17   363.0  981.85   470.9  975.21   473.2  975.22   488.2  975.66
   647.8  983.19   677.3  987.14   687.1  990.31   706.7  999.32   716.6 1002.20
   765.7 1013.95   785.3 1020.21   795.2 1021.42   834.5 1031.43   854.1 1038.46
   864.0 1039.66   883.6 1045.20   903.3 1048.70   922.9 1054.58   932.7 1056.06
#Mann= 3 , 0 , 0
       0     0.1       0   473.2   0.045       0   488.2     0.1       0
Bank Sta=   473.2,   488.2
Exp/Cntr=0.3,0.1

Type RM Length L Ch R = 1 ,19694.3,396.584,400,396.837
XS GIS Cut Line= 3
     1780654.082      397609.393     1780287.682      397335.941
     1779955.320      397025.765
#Sta/Elev= 30
       0 1098.44    29.2 1087.96    58.4 1080.43    87.5 1070.82   126.5 1063.14
   155.6 1054.42   175.1 1053.53   204.3 1047.99   223.7 1039.65   243.2 1033.03
   262.6 1023.80   291.8 1013.84   311.3 1009.97   330.7 1004.44   350.2 1001.63
   369.6  997.07   389.1  991.42   408.6  983.10   418.3  980.10   449.7  975.02
   457.2  974.63   464.7  974.79   553.9  979.37   641.0  985.27   670.0  989.08
   708.7  995.83   728.0  996.62   786.1 1002.69   834.4 1009.60   911.8 1018.35
#Mann= 3 , 0 , 0
       0     0.1       0   449.7   0.045       0   464.7     0.1       0
Bank Sta=   449.7,   464.7
Exp/Cntr=0.3,0.1

Type RM Length L Ch R = 1 ,19294.3,398.97,400,405.796
XS GIS Cut Line= 3
     1780859.242      397351.549     1780534.115      397023.057
     1780162.302      396763.004
#Sta/Elev= 30
       0 1117.87     9.8 1115.71    29.5 1108.46    49.2 1103.21    98.3 1087.22
   137.7 1076.88   167.2 1066.30   186.8 1061.91   206.5 1054.84   226.2 1050.35
   255.7 1038.87   314.7 1020.03   344.2 1006.40   373.7  997.36   403.2  985.46
   422.8  976.40   454.7  972.25   462.2  971.82   469.7  972.08   500.8  974.92
   539.4  976.17   713.2  977.95   742.1  984.48   771.1  995.07   780.8  996.67
   800.1 1004.01   838.7 1016.60   858.0 1020.12   887.0 1030.45   915.9 1037.44
#Mann= 3 , 0 , 0
       0     0.1       0   454.7   0.045       0   469.7     0.1       0
Bank Sta=   454.7,   469.7
Exp/Cntr=0.3,0.1

Type RM Length L Ch R = 1 ,18894.3,402.505,400,392.852
XS GIS Cut Line= 3
     1781104.799      397086.160     1780794.705      396744.696
     1780499.649      396399.784
#Sta/Elev= 30
       0 1100.33    29.4 1094.98    49.1 1090.28    78.5 1086.02   108.0 1079.81
   166.8 1060.35   196.3 1052.34   225.7 1040.86   245.3 1036.61   274.8 1025.13
   284.6 1022.94   314.0 1012.83   343.5 1006.67   372.9  994.29   392.6  991.87
   441.6  975.10   453.8  972.75   461.3  972.26   468.8  972.85   490.2  974.42
   586.8  977.42   664.1  978.13   702.7  982.22   731.7  987.61   770.3  991.27
   808.9  999.17   837.9 1010.46   857.2 1014.62   876.5 1021.17   915.2 1031.08
#Mann= 3 , 0 , 0
       0     0.1       0   453.8   0.045       0   468.8     0.1       0
Bank Sta=   453.8,   468.8
Exp/Cntr=0.3,0.1

Type RM Length L Ch R = 1 ,18494.3,401.086,400,395.142
XS GIS Cut Line= 3
     1781385.375      396740.365     1781031.757      396456.027
     1780658.739      396159.346
#Sta/Elev= 30
       0 1065.04    19.3 1067.82    67.6 1070.17    96.5 1074.06   154.5 1068.18
   183.4 1063.12   202.7 1057.97   231.7 1053.64   260.7 1045.20   289.6 1034.92
   299.3 1033.06   328.2 1020.05   347.6 1014.81   366.9 1002.81   386.2  992.09
   405.5  986.01   434.4  972.73   446.3  970.08   461.3  969.68   463.5  969.67
   609.4  972.57   628.8  973.92   648.3  978.14   677.5  982.81   735.8  988.10
   833.1 1007.48   852.6 1010.12   881.7 1016.31   901.2 1022.45   930.4 1028.23
#Mann= 3 , 0 , 0
       0     0.1       0   446.3   0.045       0   461.3     0.1       0
Bank Sta=   446.3,   461.3
Exp/Cntr=0.3,0.1

Type RM Length L Ch R = 1 ,18094.3,380.003,381.95,390.553
XS GIS Cut Line= 3
     1781602.942      396386.170     1781183.684      396131.353
     1780750.936      396000.368
#Sta/Elev= 30
       0  991.93    19.6  998.77    49.1 1006.62    58.9 1008.29    68.7 1007.46
    88.3 1008.96   117.7 1006.09   157.0 1004.61   186.4 1001.46   215.9  994.38
   245.3  982.96   314.0  970.80   353.2  969.74   431.7  970.77   480.8  968.55
   483.1  968.60   498.1  969.71   520.1  971.96   559.4  971.81   618.4  983.46
   667.5  990.02   756.0  994.53   785.5 1000.73   805.2 1007.69   834.6 1016.09
   844.5 1017.42   864.1 1023.94   874.0 1025.26   893.6 1031.22   942.8 1042.59
#Mann= 3 , 0 , 0
       0     0.1       0   483.1   0.045       0   498.1     0.1       0
Bank Sta=   483.1,   498.1
Exp/Cntr=0.3,0.1

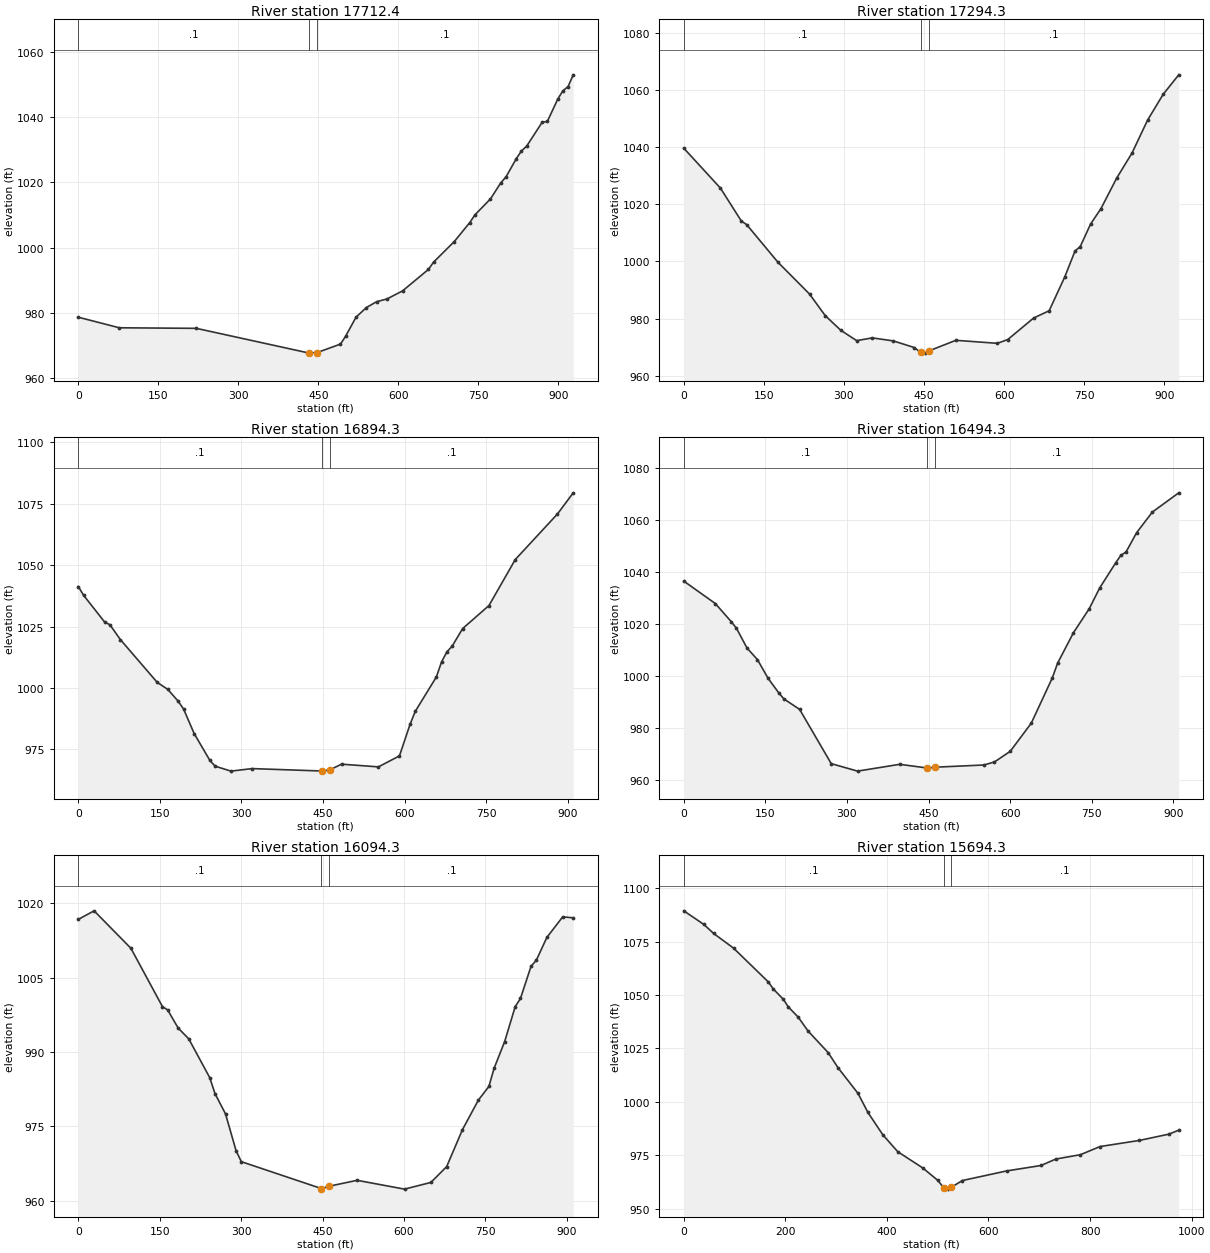
Type RM Length L Ch R = 1 ,17712.4,416.912,418.05,413.61
XS GIS Cut Line= 3
     1781707.856      396254.156     1781515.913      395943.207
     1781072.853      395596.827
#Sta/Elev= 30
       0  978.74    76.9  975.50   221.2  975.33   432.9  967.75   433.3  967.74
   447.9  967.92   491.5  970.51   501.2  972.93   520.6  978.74   540.0  981.69
   559.3  983.49   578.7  984.33   607.8  986.79   656.3  993.36   666.0  995.60
   704.8 1001.90   733.9 1007.73   743.6 1010.08   772.7 1014.97   792.1 1019.90
   801.8 1021.71   821.1 1027.30   830.8 1029.65   840.5 1031.12   869.6 1038.44
   879.3 1038.69   898.7 1045.49   908.4 1048.06   918.1 1049.35   927.8 1052.95
#Mann= 3 , 0 , 0
       0     0.1       0   432.9   0.045       0   447.9     0.1       0
Bank Sta=   432.9,   447.9
Exp/Cntr=0.3,0.1

Type RM Length L Ch R = 1 ,17294.3,407.177,400,398.391
XS GIS Cut Line= 3
     1782016.422      395850.017     1781675.758      395553.947
     1781252.233      395337.279
#Sta/Elev= 30
       0 1039.58    68.7 1025.61   107.9 1014.08   117.7 1012.87   176.6  999.66
   235.5  988.60   264.9  981.04   294.4  975.87   323.8  972.30   353.2  973.26
   392.5  972.20   431.7  969.89   443.8  968.15   451.3  967.93   458.8  968.68
   509.6  972.41   587.3  971.36   606.7  972.66   655.2  980.19   684.4  982.75
   713.5  994.53   732.9 1003.66   742.6 1005.18   762.0 1013.07   781.4 1018.45
   810.6 1029.03   839.7 1037.93   868.8 1049.41   897.9 1058.41   927.1 1065.23
#Mann= 3 , 0 , 0
       0     0.1       0   443.8   0.045       0   458.8     0.1       0
Bank Sta=   443.8,   458.8
Exp/Cntr=0.3,0.1

Type RM Length L Ch R = 1 ,16894.3,396.371,400,403.629
XS GIS Cut Line= 3
     1782196.610      395353.560     1781777.309      395176.890
     1781358.009      395000.221
#Sta/Elev= 30
       0 1041.27     9.7 1037.72    48.4 1026.83    58.1 1025.72    77.4 1019.67
   145.2 1002.26   164.6  999.42   183.9  994.55   193.6  991.43   213.0  981.48
   242.0  970.51   251.7  968.18   280.7  966.18   319.5  967.21   447.5  966.23
   462.5  966.71   484.0  969.01   551.8  967.91   590.5  972.38   609.9  985.17
   619.6  990.50   658.3 1004.47   668.0 1010.66   677.7 1014.69   687.3 1016.99
   706.7 1024.17   755.1 1033.54   803.5 1052.25   881.0 1070.77   910.0 1079.37
#Mann= 3 , 0 , 0
       0     0.1       0   447.5   0.045       0   462.5     0.1       0
Bank Sta=   447.5,   462.5
Exp/Cntr=0.3,0.1

Type RM Length L Ch R = 1 ,16494.3,400.862,400,396.639
XS GIS Cut Line= 3
     1782341.200      395061.416     1781955.683      394819.752
     1781570.166      394578.088
#Sta/Elev= 30
       0 1036.48    58.1 1027.83    87.1 1020.90    96.8 1018.36   116.2 1010.73
   135.5 1006.25   154.9  999.10   174.3  993.57   183.9  991.17   213.0  987.11
   271.1  966.24   319.5  963.36   396.9  965.98   447.5  964.57   462.5  964.88
   551.8  965.72   571.2  966.89   600.2  970.98   638.9  981.82   677.7  999.30
   687.3 1004.91   716.4 1016.61   745.4 1025.84   764.8 1033.90   793.8 1043.43
   803.5 1046.37   813.2 1047.72   832.6 1055.13   861.6 1063.06   910.0 1070.45
#Mann= 3 , 0 , 0
       0     0.1       0   447.5   0.045       0   462.5     0.1       0
Bank Sta=   447.5,   462.5
Exp/Cntr=0.3,0.1

Type RM Length L Ch R = 1 ,16094.3,410.25,400,387.213
XS GIS Cut Line= 3
     1782551.235      394701.363     1782156.548      394474.516
     1781738.263      394291.857
#Sta/Elev= 30
       0 1016.77    29.1 1018.50    96.9 1010.95   155.0  999.18   164.7  998.50
   184.0  994.84   203.4  992.68   242.1  984.85   251.8  981.63   271.2  977.53
   290.6  970.12   300.3  967.89   447.7  962.47   462.7  962.95   513.5  964.13
   600.9  962.35   649.5  963.70   678.6  966.90   707.7  974.36   736.9  980.30
   756.3  983.06   766.0  986.75   785.4  992.13   804.8  999.17   814.5 1000.82
   834.0 1007.32   843.7 1008.53   863.1 1013.13   892.2 1017.27   911.7 1017.10
#Mann= 3 , 0 , 0
       0     0.1       0   447.7   0.045       0   462.7     0.1       0
Bank Sta=   447.7,   462.7
Exp/Cntr=0.3,0.1

Type RM Length L Ch R = 1 ,15694.3,391.058,400,418.885
XS GIS Cut Line= 3
     1782718.941      394122.254     1782199.995      394099.470
     1781751.939      394179.329
#Sta/Elev= 30
       0 1089.44    39.2 1083.12    58.8 1078.84    98.0 1071.96   166.6 1056.10
   176.4 1052.79   196.0 1048.01   205.8 1044.45   225.4 1039.61   245.0 1033.06
   284.2 1023.05   303.8 1015.92   343.0 1003.95   362.6  994.99   392.0  984.52
   421.4  976.60   470.4  969.04   499.8  963.27   511.9  959.75   519.4  959.09
   526.9  959.97   548.5  963.11   635.6  967.61   703.4  970.16   732.5  973.18
   780.9  975.21   819.6  979.03   897.1  981.90   955.2  984.84   974.6  986.69
#Mann= 3 , 0 , 0
       0     0.1       0   511.9   0.045       0   526.9     0.1       0
Bank Sta=   511.9,   526.9
Exp/Cntr=0.3,0.1