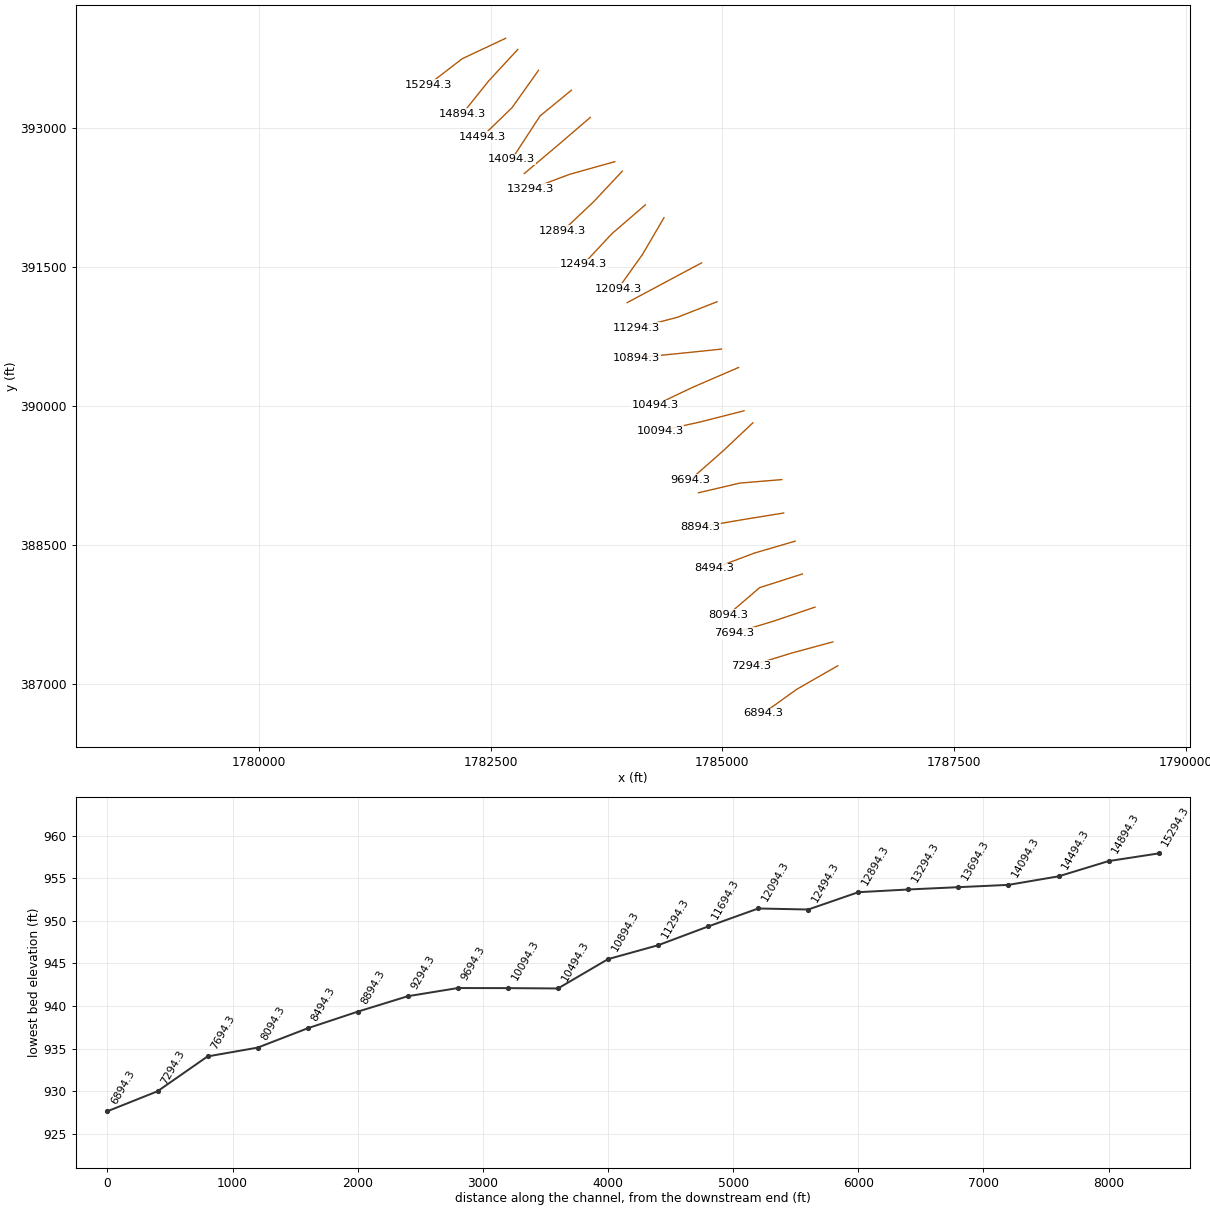
HEC-RAS study LtlPwPwCrk.prj: LtlPwPwCrk

--- LtlPwPwCrk.g01 (geometry) --- (continued)

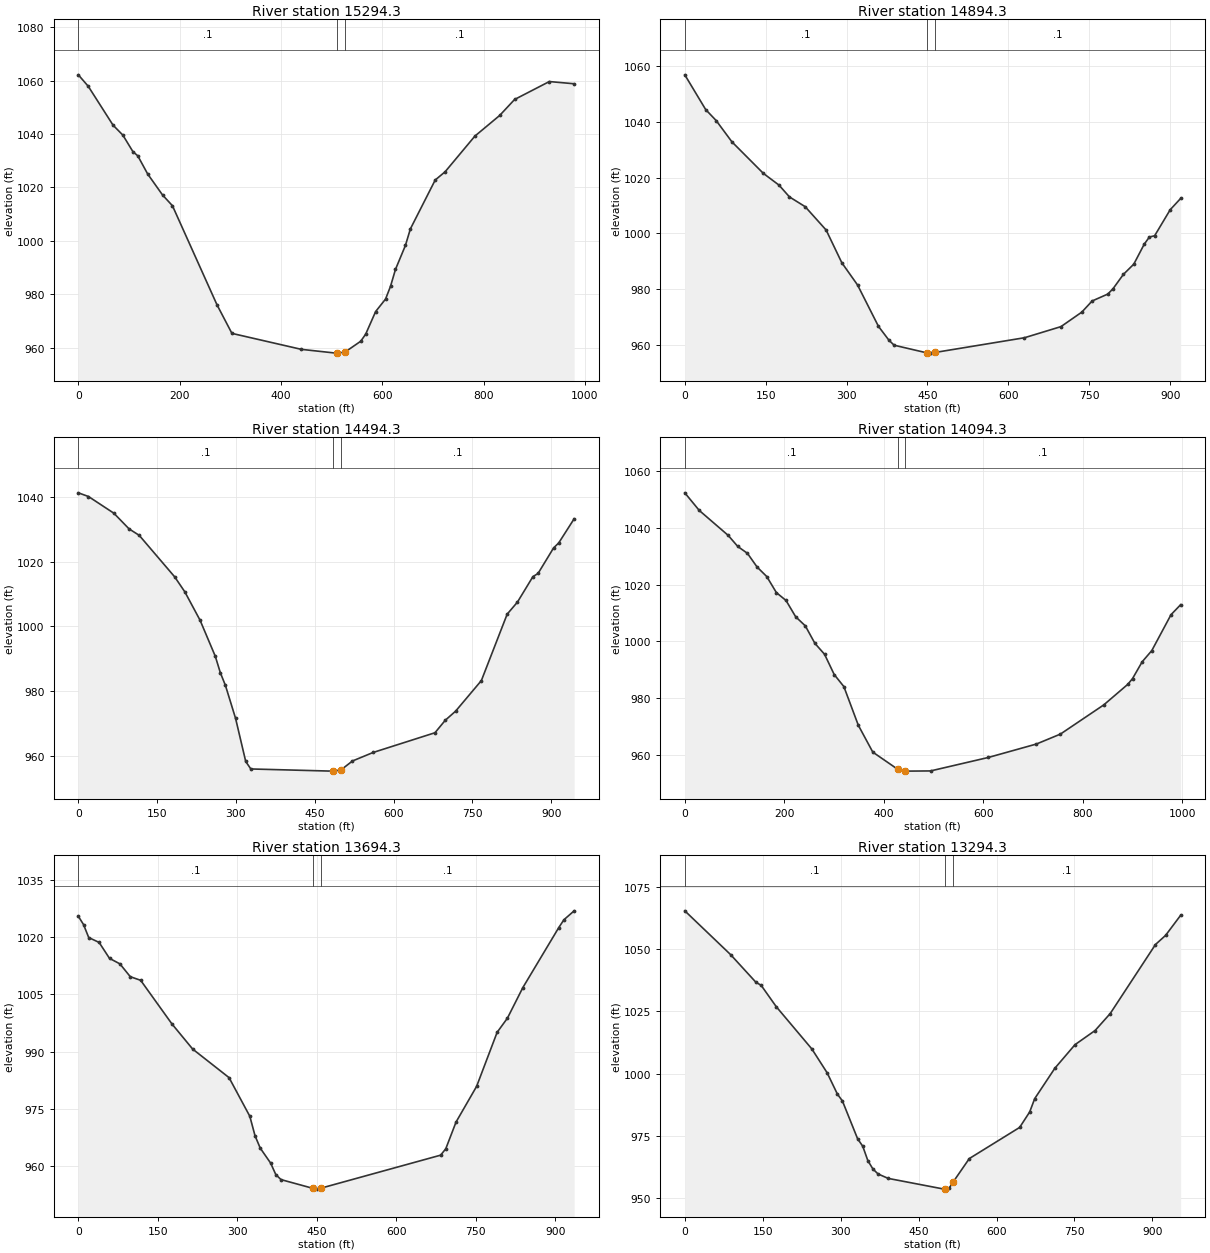
Type RM Length L Ch R = 1 ,15294.3,391.152,400,405.603
XS GIS Cut Line= 3
     1782662.647      393963.997     1782193.567      393743.426
     1781828.724      393462.538
#Sta/Elev= 30
       0 1062.19    19.6 1057.89    68.5 1043.34    88.0 1039.57   107.6 1033.45
   117.4 1031.82   136.9 1025.03   166.3 1017.15   185.8 1013.13   273.8  975.98
   303.2  965.30   440.1  959.32   508.6  957.90   510.9  957.90   525.9  958.22
   557.5  962.36   567.3  965.03   586.9  973.48   606.5  978.17   616.3  982.95
   626.1  989.29   645.7  998.25   655.5 1004.46   704.5 1022.77   724.1 1025.87
   782.9 1039.24   831.8 1046.97   861.2 1052.95   929.8 1059.67   978.8 1058.84
#Mann= 3 , 0 , 0
       0     0.1       0   510.9   0.045       0   525.9     0.1       0
Bank Sta=   510.9,   525.9
Exp/Cntr=0.3,0.1

Type RM Length L Ch R = 1 ,14894.3,397.699,400,396.489
XS GIS Cut Line= 3
     1782794.489      393844.300     1782484.488      393509.638
     1782194.472      393148.393
#Sta/Elev= 30
       0 1056.97    38.8 1044.47    58.2 1040.54    87.4 1032.89   145.6 1021.58
   174.7 1017.35   194.1 1013.11   223.2 1009.61   262.1 1001.21   291.2  989.45
   320.3  981.49   359.1  966.62   378.5  961.65   388.2  959.84   448.7  957.10
   456.2  957.00   463.7  957.23   629.9  962.53   697.5  966.52   736.1  971.72
   755.4  975.74   784.3  978.21   794.0  980.12   813.3  985.29   832.6  988.97
   851.9  996.13   861.5  998.72   871.2  999.16   900.1 1008.52   919.4 1012.56
#Mann= 3 , 0 , 0
       0     0.1       0   448.7   0.045       0   463.7     0.1       0
Bank Sta=   448.7,   463.7
Exp/Cntr=0.3,0.1

Type RM Length L Ch R = 1 ,14494.3,405.71,400,405.733
XS GIS Cut Line= 3
     1783018.263      393619.534     1782733.431      393217.907
     1782409.638      392903.459
#Sta/Elev= 30
       0 1041.27    19.3 1040.13    67.6 1034.97    96.5 1030.13   115.9 1028.12
   183.4 1015.28   202.7 1010.65   231.7 1001.87   260.7  990.72   270.3  985.63
   280.0  981.70   299.3  971.51   318.6  958.19   328.3  955.88   482.7  955.21
   484.9  955.22   499.9  955.59   521.8  958.35   561.1  960.98   678.8  967.08
   698.4  970.94   718.1  973.76   767.1  983.21   816.2 1003.75   835.8 1007.49
   865.2 1015.35   875.0 1016.34   904.5 1024.22   914.3 1025.77   943.7 1033.25
#Mann= 3 , 0 , 0
       0     0.1       0   484.9   0.045       0   499.9     0.1       0
Bank Sta=   484.9,   499.9
Exp/Cntr=0.3,0.1

Type RM Length L Ch R = 1 ,14094.3,399.618,400,392.903
XS GIS Cut Line= 3
     1783372.216      393404.295     1783034.991      393127.541
     1782728.469      392657.689
#Sta/Elev= 30
       0 1052.44    29.1 1046.22    87.2 1037.43   106.6 1033.50   126.0 1031.08
   145.4 1026.25   164.8 1022.90   184.2 1017.22   203.6 1014.44   223.0 1008.69
   242.4 1005.48   261.7  999.30   281.1  995.45   300.5  988.30   319.9  984.05
   349.0  970.39   378.1  960.92   428.8  954.79   443.8  954.21   494.3  954.28
   610.4  959.03   707.1  963.77   755.4  967.28   842.5  977.57   890.9  984.84
   900.5  986.88   919.9  992.81   939.2  996.75   977.9 1009.43   997.2 1012.95
#Mann= 3 , 0 , 0
       0     0.1       0   428.8   0.045       0   443.8     0.1       0
Bank Sta=   428.8,   443.8
Exp/Cntr=0.3,0.1

Type RM Length L Ch R = 1 ,13694.3,409.312,400,392.834
XS GIS Cut Line= 3
     1783576.483      393111.578     1783234.276      392817.945
     1782864.056      392505.530
#Sta/Elev= 30
       0 1025.52     9.8 1023.35    19.6 1019.94    39.2 1018.66    58.8 1014.48
    78.4 1013.04    98.0 1009.67   117.6 1008.72   176.4  997.31   215.7  990.68
   284.3  983.19   323.5  973.05   333.3  967.95   343.1  964.71   362.7  960.78
   372.5  957.76   382.3  956.44   443.4  954.11   450.9  953.94   458.4  954.22
   683.4  962.85   693.1  964.52   712.5  971.54   751.3  980.90   790.0  995.08
   809.4  998.79   838.5 1006.81   906.3 1022.56   916.0 1024.61   935.3 1026.95
#Mann= 3 , 0 , 0
       0     0.1       0   443.4   0.045       0   458.4     0.1       0
Bank Sta=   443.4,   458.4
Exp/Cntr=0.3,0.1

Type RM Length L Ch R = 1 ,13294.3,387.561,400,409.09
XS GIS Cut Line= 3
     1783840.920      392634.091     1783350.959      392496.580
     1782934.068      392339.674
#Sta/Elev= 30
       0 1065.28    88.1 1047.73   137.0 1036.60   146.8 1035.44   176.2 1026.79
   244.7 1009.84   274.0 1000.31   293.6  991.82   303.4  989.01   332.7  973.81
   342.5  970.88   352.3  965.10   362.1  961.74   371.9  959.76   391.5  957.97
   499.1  953.67   501.4  953.77   508.9  954.09   516.4  956.51   547.6  965.93
   644.5  978.42   663.8  984.63   673.5  989.98   712.2 1002.14   751.0 1011.60
   789.7 1017.28   818.8 1024.08   905.9 1051.77   925.3 1055.42   954.3 1063.48
#Mann= 3 , 0 , 0
       0     0.1       0   501.4   0.045       0   516.4     0.1       0
Bank Sta=   501.4,   516.4
Exp/Cntr=0.3,0.1

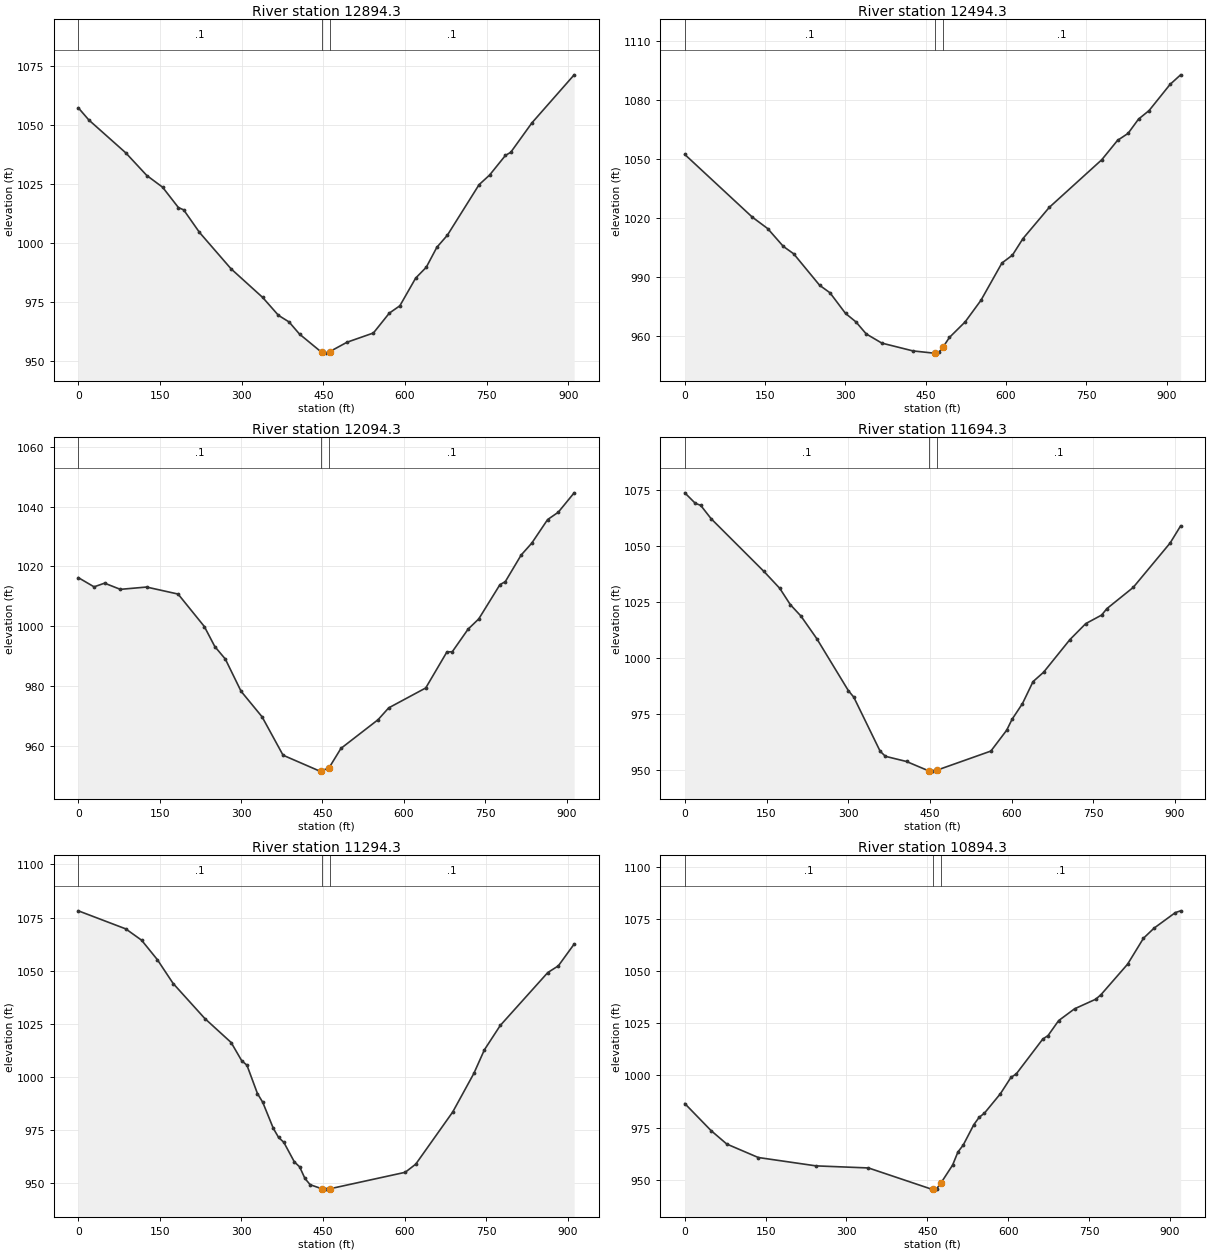
Type RM Length L Ch R = 1 ,12894.3,402.38,400,401.455
XS GIS Cut Line= 3
     1783921.178      392531.136     1783610.035      392199.408
     1783278.127      391886.621
#Sta/Elev= 30
       0 1057.37    19.4 1052.19    87.1 1038.29   125.8 1028.67   154.8 1023.71
   183.9 1015.06   193.5 1014.11   222.6 1004.53   280.6  989.09   338.7  976.95
   367.7  969.36   387.1  966.58   406.4  961.41   447.3  953.64   454.8  953.35
   462.3  954.04   493.6  957.97   542.1  961.89   571.3  970.31   590.7  973.43
   619.8  985.19   639.2  989.76   658.6  998.21   678.0 1003.36   736.2 1024.78
   755.6 1028.87   784.7 1037.20   794.4 1038.51   833.3 1050.99   910.9 1071.36
#Mann= 3 , 0 , 0
       0     0.1       0   447.3   0.045       0   462.3     0.1       0
Bank Sta=   447.3,   462.3
Exp/Cntr=0.3,0.1

Type RM Length L Ch R = 1 ,12494.3,392.532,400,402.989
XS GIS Cut Line= 3
     1784170.154      392168.253     1783810.639      391858.539
     1783502.391      391528.562
#Sta/Elev= 30
       0 1052.20   125.9 1020.42   154.9 1014.54   184.0 1005.52   203.4 1001.75
   251.8  985.78   271.2  981.95   300.2  971.49   319.6  967.20   338.9  961.07
   368.0  956.41   426.1  952.45   464.8  951.32     467  951.41   474.5  951.70
     482  954.24   494.2  959.27   523.6  967.17   553.1  978.12   592.3  997.06
   612.0 1001.09   631.6 1009.47   680.7 1025.31   778.8 1049.51   808.3 1059.36
   827.9 1062.89   847.5 1070.16   867.2 1074.49   906.4 1087.77   926.1 1092.63
#Mann= 3 , 0 , 0
       0     0.1       0     467   0.045       0     482     0.1       0
Bank Sta=     467,     482
Exp/Cntr=0.3,0.1

Type RM Length L Ch R = 1 ,12094.3,412.596,400,389.452
XS GIS Cut Line= 3
     1784370.789      392029.379     1784141.262      391636.719
     1783875.051      391262.622
#Sta/Elev= 30
       0 1016.23    29.0 1013.15    48.4 1014.38    77.4 1012.31   125.8 1013.08
   183.9 1010.73   232.3  999.86   251.6  993.15   271.0  988.96   300.0  978.18
   338.7  969.63   377.4  956.77   445.1  951.44   447.3  951.45   462.3  952.59
   484.1  959.05   552.5  968.66   572.1  972.62   640.4  979.29   679.5  991.37
   689.3  991.41   718.6  999.01   738.1 1002.40   777.2 1013.89   787.0 1014.87
   816.3 1023.80   835.8 1027.77   865.1 1035.68   884.7 1038.13   914.0 1044.63
#Mann= 3 , 0 , 0
       0     0.1       0   447.3   0.045       0   462.3     0.1       0
Bank Sta=   447.3,   462.3
Exp/Cntr=0.3,0.1

Type RM Length L Ch R = 1 ,11694.3,402.595,400,394.67
XS GIS Cut Line= 3
     1784776.670      391542.359     1784374.868      391327.966
     1783973.767      391113.573
#Sta/Elev= 30
       0 1073.61    19.4 1068.90    29.1 1068.04    48.4 1062.03   145.3 1038.50
   174.4 1030.94   193.8 1023.65   213.2 1018.58   242.2 1008.52   300.4  985.22
   310.1  982.41   358.5  958.26   368.2  955.95   407.0  953.63   447.9  949.43
   455.4  949.33   462.9  949.76   561.9  958.29   590.9  967.61   600.6  972.41
   619.9  979.51   639.3  989.31   658.6  993.48   707.0 1008.08   736.0 1015.20
   765.1 1019.01   774.8 1021.89   823.1 1031.35   890.9 1051.19   910.2 1058.85
#Mann= 3 , 0 , 0
       0     0.1       0   447.9   0.045       0   462.9     0.1       0
Bank Sta=   447.9,   462.9
Exp/Cntr=0.3,0.1

Type RM Length L Ch R = 1 ,11294.3,406.123,400,396.493
XS GIS Cut Line= 3
     1784942.427      391123.142     1784518.651      390956.368
     1784077.143      390840.718
#Sta/Elev= 30
       0 1078.17    87.2 1069.67   116.3 1064.35   145.3 1055.18   174.4 1043.95
   232.6 1027.47   281.0 1016.17   300.4 1007.62   310.1 1005.46   329.4  992.12
   339.1  988.03   358.5  975.79   368.2  971.50   377.9  969.16   397.3  959.94
   407.0  957.61   416.7  952.16   426.3  949.22   447.9  947.29   455.4  947.13
   462.9  947.31   601.1  955.05   620.5  958.90   688.5  983.46   727.3 1001.59
   746.7 1012.71   775.9 1024.19   863.3 1049.11   882.7 1052.26   911.8 1062.52
#Mann= 3 , 0 , 0
       0     0.1       0   447.9   0.045       0   462.9     0.1       0
Bank Sta=   447.9,   462.9
Exp/Cntr=0.3,0.1

Type RM Length L Ch R = 1 ,10894.3,393.145,400,407.773
XS GIS Cut Line= 3
     1784990.364      390612.187     1784525.491      390564.253
     1784075.116      390519.895
#Sta/Elev= 30
       0  986.52    48.7  973.57    77.9  967.11   136.3  960.66   243.4  956.65
   340.8  955.65   457.6  945.50   459.8  945.54   467.3  945.70   474.8  948.27
   496.9  957.05   506.7  963.29   516.5  966.60   536.2  976.39   546.0  979.90
   555.9  981.92   585.4  991.19   605.1  999.06   614.9 1000.71   664.1 1017.43
   673.9 1019.11   693.6 1026.30   723.1 1031.94   762.5 1036.56   772.3 1038.77
   821.5 1053.34   851.0 1065.79   870.7 1070.63   910.1 1078.07   919.9 1078.92
#Mann= 3 , 0 , 0
       0     0.1       0   459.8   0.045       0   474.8     0.1       0
Bank Sta=   459.8,   474.8
Exp/Cntr=0.3,0.1

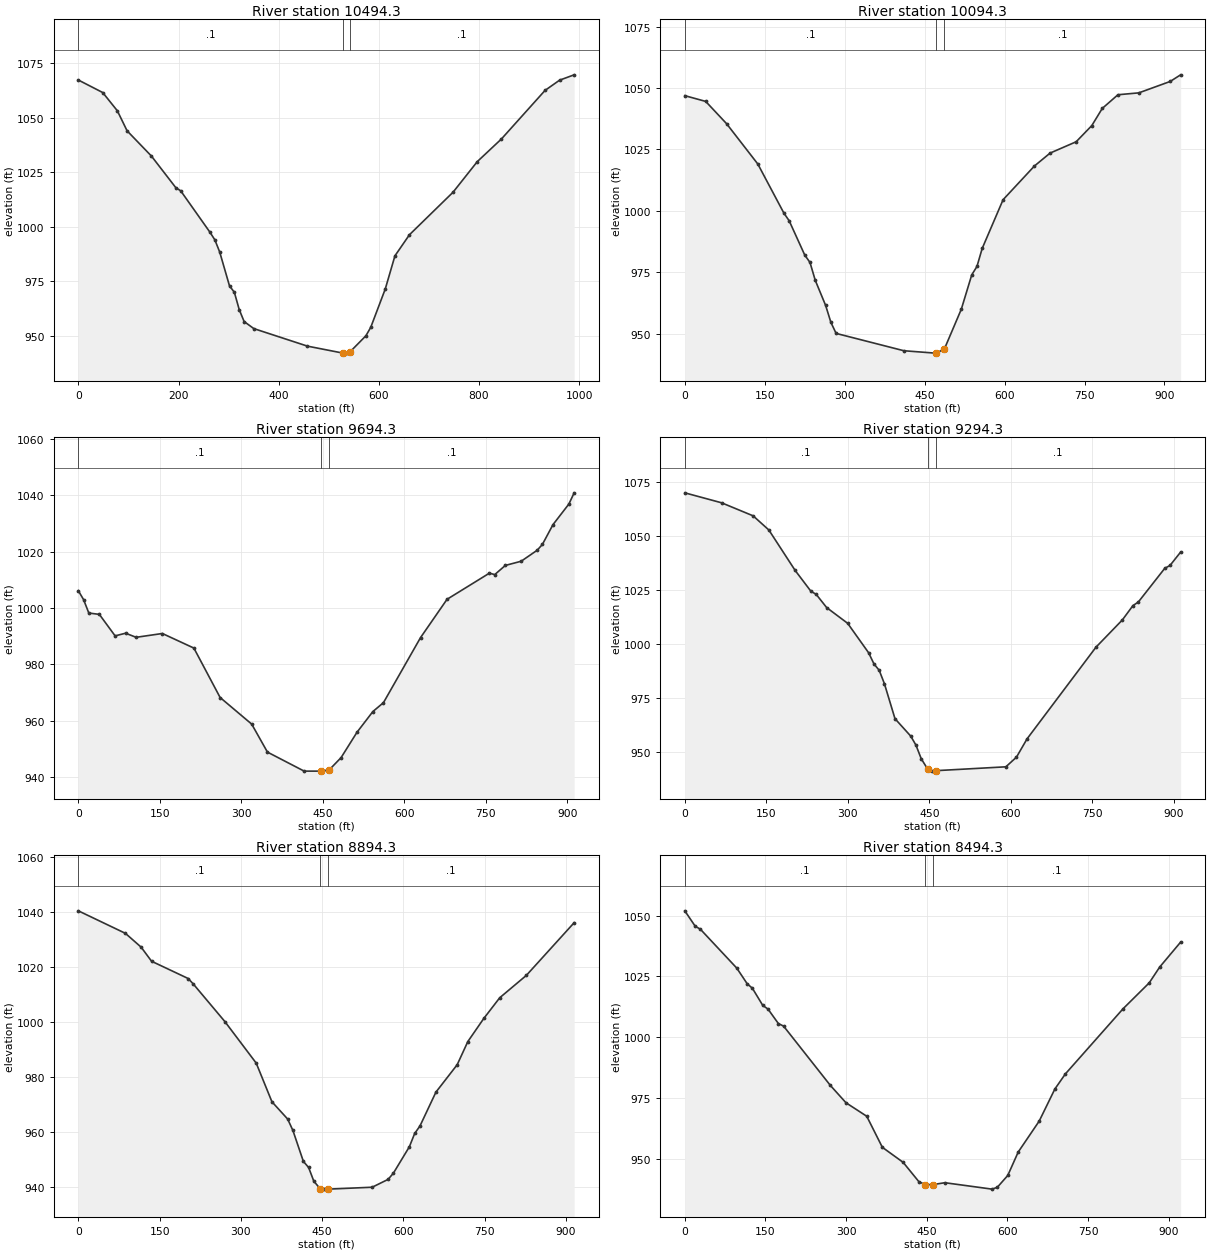
Type RM Length L Ch R = 1 ,10494.3,403.508,400,394.951
XS GIS Cut Line= 3
     1785175.073      390413.977     1784683.507      390201.794
     1784273.055      390006.713
#Sta/Elev= 30
       0 1067.29    48.7 1061.55    77.9 1053.18    97.3 1044.01   146.0 1032.40
   194.7 1017.90   204.4 1016.48   262.8  997.49   272.6  993.98   282.3  988.38
   301.8  972.89   311.5  969.96   321.2  962.03   331.0  956.54   350.4  953.30
   457.5  945.26   527.9  942.09   535.4  942.06   542.9  942.75   574.1  950.01
   583.8  953.89   612.8  971.48   632.1  986.68   661.1  996.35   748.1 1015.84
   796.5 1029.87   844.8 1040.28   931.8 1062.53   960.9 1067.23   989.9 1069.67
#Mann= 3 , 0 , 0
       0     0.1       0   527.9   0.045       0   542.9     0.1       0
Bank Sta=   527.9,   542.9
Exp/Cntr=0.3,0.1

Type RM Length L Ch R = 1 ,10094.3,388.581,400,411.374
XS GIS Cut Line= 3
     1785234.243      389947.227     1784769.548      389828.477
     1784329.551      389731.050
#Sta/Elev= 30
       0 1046.92    39.2 1044.58    78.3 1035.53   137.0 1019.09   186.0  999.07
   195.8  996.00   225.1  982.01   234.9  979.02   244.7  971.79   264.3  961.49
   274.1  954.63   283.9  950.13   411.1  943.07   469.8  942.10   472.1  942.13
   487.1  943.81   518.8  959.97   538.4  973.96   548.2  977.40   558.0  984.73
   597.2 1004.56   656.0 1018.28   685.4 1023.54   734.3 1028.15   763.7 1034.75
   783.3 1041.73   812.7 1047.29   851.9 1048.06   910.7 1052.70   930.3 1055.40
#Mann= 3 , 0 , 0
       0     0.1       0   472.1   0.045       0   487.1     0.1       0
Bank Sta=   472.1,   487.1
Exp/Cntr=0.3,0.1

Type RM Length L Ch R = 1 ,9694.3,415.21,400,388.902
XS GIS Cut Line= 3
     1785328.998      389816.732     1784998.056      389505.329
     1784653.717      389202.881
#Sta/Elev= 30
       0 1006.09     9.7 1002.92    19.3  998.18    38.7  997.70    67.7  990.08
    87.0  991.02   106.4  989.57   154.7  990.92   212.7  985.75   261.0  968.22
   319.1  958.79   348.1  948.86   415.7  942.11   446.9  942.11   461.9  942.57
   483.7  946.91   512.9  955.88   542.2  963.24   561.7  966.40   629.9  989.46
   678.7 1003.05   756.7 1012.32   766.5 1011.81   786.0 1015.06   815.2 1016.55
   844.5 1020.43   854.2 1022.50   873.7 1029.52   903.0 1036.84   912.7 1040.81
#Mann= 3 , 0 , 0
       0     0.1       0   446.9   0.045       0   461.9     0.1       0
Bank Sta=   446.9,   461.9
Exp/Cntr=0.3,0.1

Type RM Length L Ch R = 1 ,9294.3,398.274,400,398.585
XS GIS Cut Line= 3
     1785641.907      389205.076     1785189.013      389167.436
     1784743.025      389062.871
#Sta/Elev= 30
       0 1070.16    67.7 1065.54   125.7 1059.50   154.7 1052.93   203.1 1034.18
   232.1 1024.53   241.7 1023.13   261.1 1016.96   299.7 1009.68   338.4  995.98
   348.1  990.86   357.8  987.88   367.4  981.65   386.8  965.47   415.8  957.38
   425.4  953.21   435.1  946.91     447  942.07   454.5  941.15     462  941.36
   590.9  943.15   610.4  947.63   629.9  956.12   756.6  998.57   805.3 1011.25
   824.8 1017.90   834.6 1019.52   883.3 1035.16   893.0 1036.50   912.5 1042.69
#Mann= 3 , 0 , 0
       0     0.1       0     447   0.045       0     462     0.1       0
Bank Sta=     447,     462
Exp/Cntr=0.3,0.1

Type RM Length L Ch R = 1 ,8894.3,397.006,400,404.57
XS GIS Cut Line= 3
     1785661.392      388844.616     1785213.194      388772.069
     1784758.635      388693.689
#Sta/Elev= 30
       0 1040.35    86.9 1032.18   115.9 1027.17   135.2 1022.05   202.9 1015.77
   212.5 1013.73   270.5 1000.16   328.4  985.07   357.4  971.04   386.4  964.78
   396.1  960.64   415.4  949.42   425.1  947.20   434.7  942.23   446.5  939.46
   454.0  939.34   461.5  939.34   542.4  940.03   571.8  942.87   581.6  945.13
   611.1  954.72   620.9  959.54   630.7  962.27   660.1  974.54   699.4  984.50
   719.0  992.89   748.5 1001.29   777.9 1008.80   827.0 1016.91   915.3 1036.05
#Mann= 3 , 0 , 0
       0     0.1       0   446.5   0.045       0   461.5     0.1       0
Bank Sta=   446.5,   461.5
Exp/Cntr=0.3,0.1

Type RM Length L Ch R = 1 ,8494.3,399.905,400,407.835
XS GIS Cut Line= 3
     1785784.827      388540.863     1785348.739      388413.411
     1784911.117      388248.663
#Sta/Elev= 30
       0 1052.04    19.3 1045.71    29.0 1044.46    96.7 1028.43   116.0 1021.99
   125.7 1020.14   145.0 1013.07   154.7 1011.57   174.0 1005.60   183.7 1004.54
   270.7  980.10   299.7  972.97   338.3  967.41   367.3  954.62   406.0  948.42
   435.0  940.52   446.8  939.25   461.8  939.27   483.6  940.03   571.2  937.39
   581.0  938.13   600.5  943.02   619.9  952.66   658.9  965.40   688.1  978.64
   707.6  984.85   814.8 1011.68   863.5 1022.36   883.0 1028.88   921.9 1039.15
#Mann= 3 , 0 , 0
       0     0.1       0   446.8   0.045       0   461.8     0.1       0
Bank Sta=   446.8,   461.8
Exp/Cntr=0.3,0.1

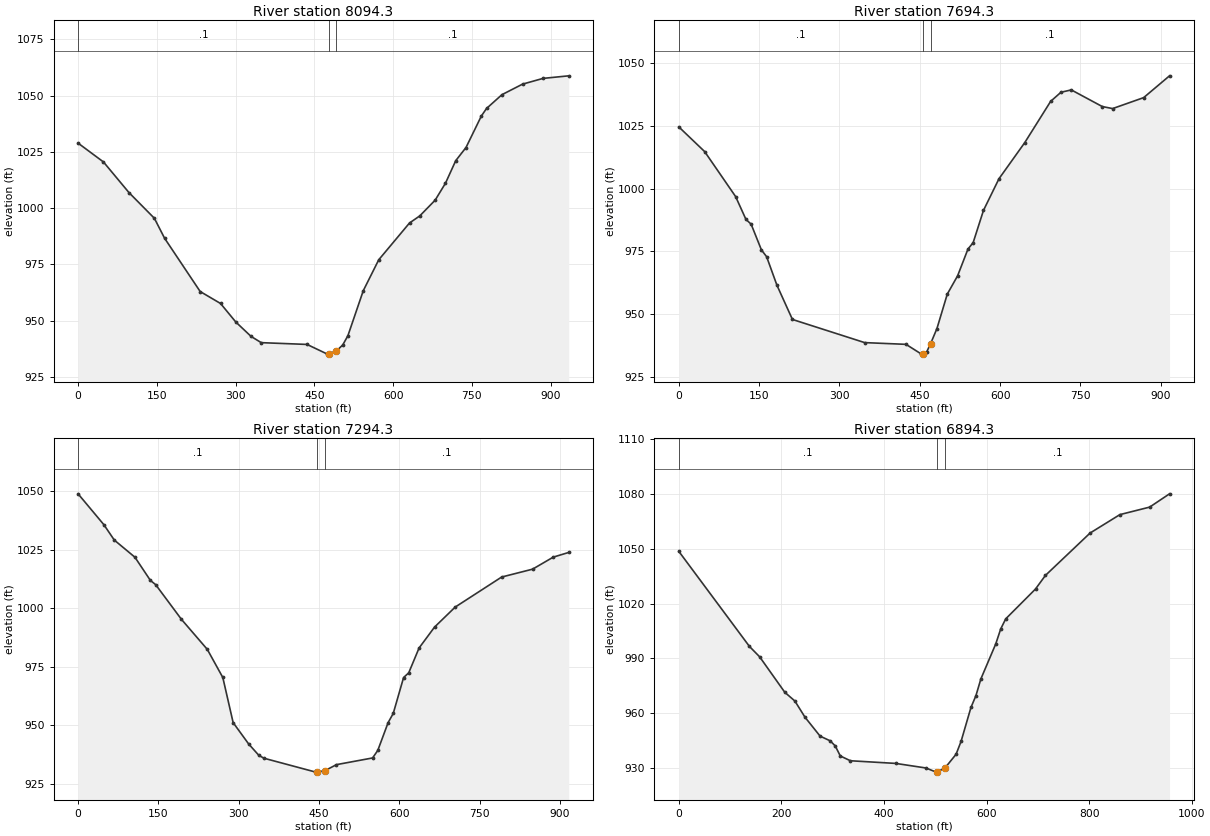
Type RM Length L Ch R = 1 ,8094.3,399.152,400,390.617
XS GIS Cut Line= 3
     1785863.426      388187.286     1785402.002      388039.668
     1785060.806      387746.571
#Sta/Elev= 30
       0 1028.92    48.4 1020.53    96.9 1006.93   145.3  995.50   164.7  986.65
   232.5  962.95   271.3  957.63   300.4  949.38   329.4  943.00   348.8  940.22
   436.0  939.43   474.8  935.12     477  935.21     492  936.55   504.0  939.20
   513.8  943.31   543.1  963.33   572.5  977.05   631.1  993.41   650.7  996.57
   680.0 1003.58   699.6 1011.10   719.1 1021.10   738.7 1026.97   768.0 1041.00
   777.8 1044.32   807.1 1050.45   846.3 1055.13   885.4 1057.69   934.3 1058.83
#Mann= 3 , 0 , 0
       0     0.1       0     477   0.045       0     492     0.1       0
Bank Sta=     477,     492
Exp/Cntr=0.3,0.1

Type RM Length L Ch R = 1 ,7694.3,401.415,400,400.052
XS GIS Cut Line= 3
     1786000.364      387829.821     1785562.059      387681.482
     1785128.035      387549.822
#Sta/Elev= 30
       0 1024.64    48.2 1014.81   106.0  996.89   125.3  987.79   135.0  985.88
   154.2  975.62   163.9  972.92   183.2  961.53   212.1  947.91   347.0  938.68
   424.2  937.99   453.1  934.09   455.2  934.27   462.7  934.92   470.2  938.29
   482.0  944.30   501.3  958.02   520.6  965.32   539.9  975.96   549.6  978.53
   568.9  991.39   597.8 1003.98   646.1 1018.43   694.3 1034.83   713.6 1038.46
   732.9 1039.40   790.8 1032.76   810.1 1031.96   868.0 1036.32   916.3 1045.01
#Mann= 3 , 0 , 0
       0     0.1       0   455.2   0.045       0   470.2     0.1       0
Bank Sta=   455.2,   470.2
Exp/Cntr=0.3,0.1

Type RM Length L Ch R = 1 ,7294.3,394.107,400,407.477
XS GIS Cut Line= 3
     1786191.641      387454.365     1785753.767      387335.783
     1785311.472      387200.011
#Sta/Elev= 30
       0 1048.80    48.3 1035.59    67.6 1029.07   106.2 1021.73   135.1 1011.82
   144.8 1010.06   193.0  995.23   241.3  982.41   270.3  970.40   289.6  951.13
   318.5  942.04   337.8  937.11   347.5  935.91   444.0  930.00   446.1  930.01
   461.1  930.64   482.6  933.20   550.0  936.05   559.7  939.26   579.0  951.13
   588.6  955.07   607.9  970.38   617.5  972.39   636.8  982.98   665.7  991.91
   704.3 1000.46   791.0 1013.28   848.8 1016.64   887.4 1021.78   916.3 1023.78
#Mann= 3 , 0 , 0
       0     0.1       0   446.1   0.045       0   461.1     0.1       0
Bank Sta=   446.1,   461.1
Exp/Cntr=0.3,0.1

Type RM Length L Ch R = 1 ,6894.3,397.57,400,402.18
XS GIS Cut Line= 3
     1786245.825      387197.708     1785802.146      386943.114
     1785440.207      386683.753
#Sta/Elev= 30
       0 1048.54   137.7  996.48   157.4  990.86   206.6  971.38   226.3  966.59
   245.9  957.77   275.4  947.38   295.1  944.80   305.0  942.00   314.8  936.52
   334.5  933.89   423.0  932.43   482.0  929.92   501.7  927.66     504  927.81
     519  929.94   540.6  937.45   550.3  944.46   569.6  963.07   579.3  969.52
   589.0  978.74   618.0  997.90   627.7 1006.12   637.4 1011.60   695.5 1027.95
   714.8 1035.38   801.9 1058.59   860.0 1068.68   918.1 1072.80   956.8 1080.07
#Mann= 3 , 0 , 0
       0     0.1       0     504   0.045       0     519     0.1       0
Bank Sta=     504,     519
Exp/Cntr=0.3,0.1