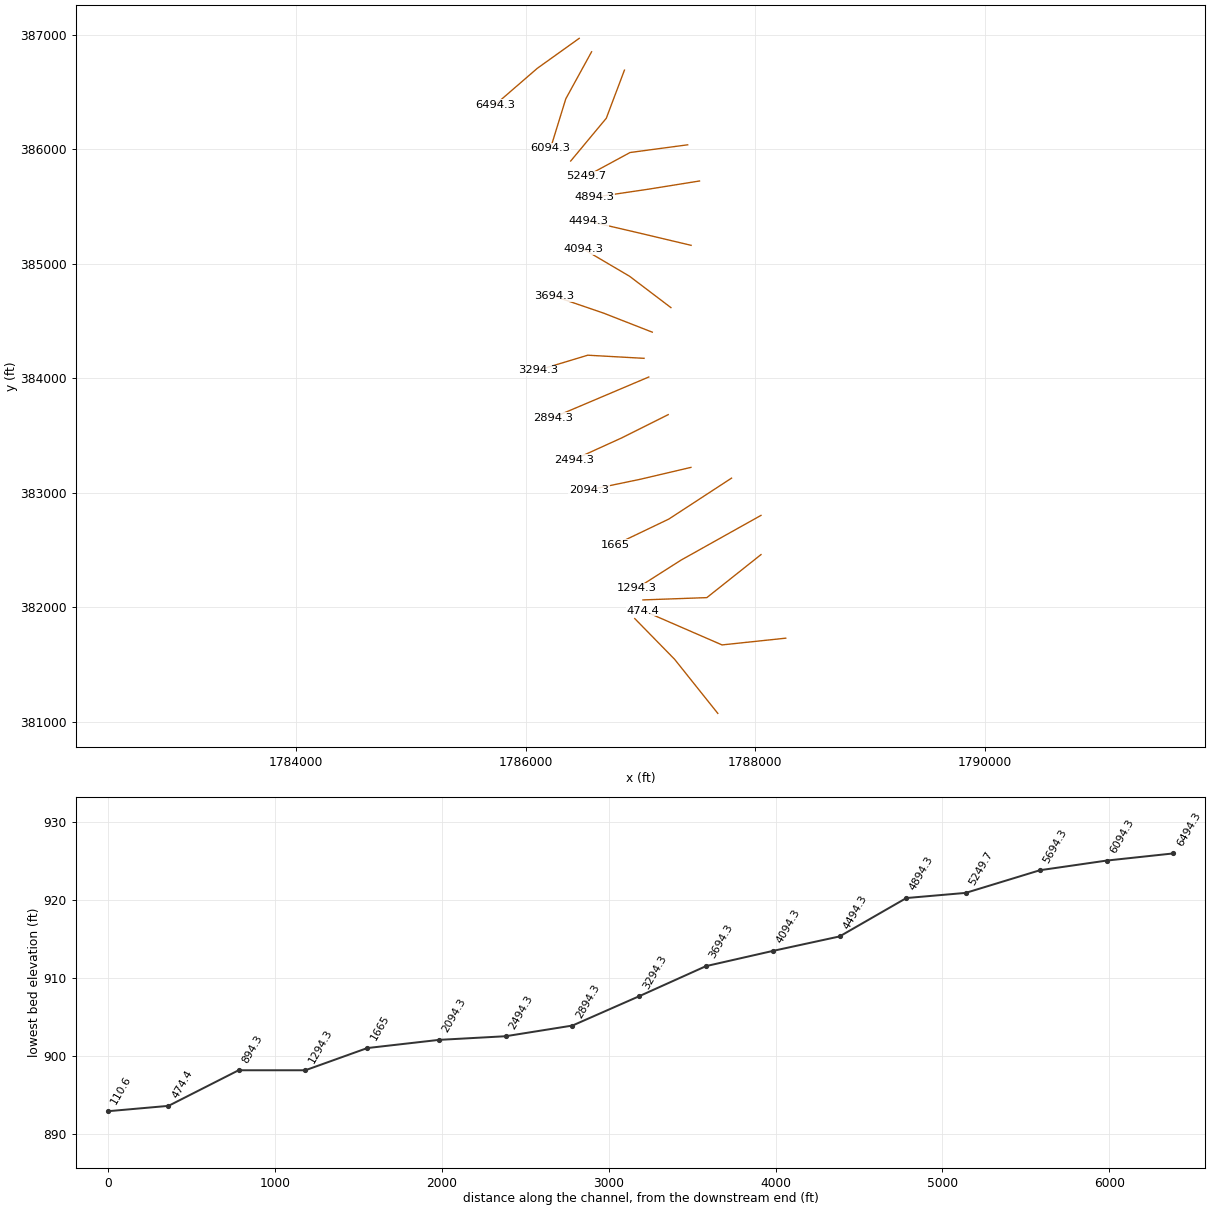
HEC-RAS study LtlPwPwCrk.prj: LtlPwPwCrk

--- LtlPwPwCrk.g01 (geometry) --- (continued)

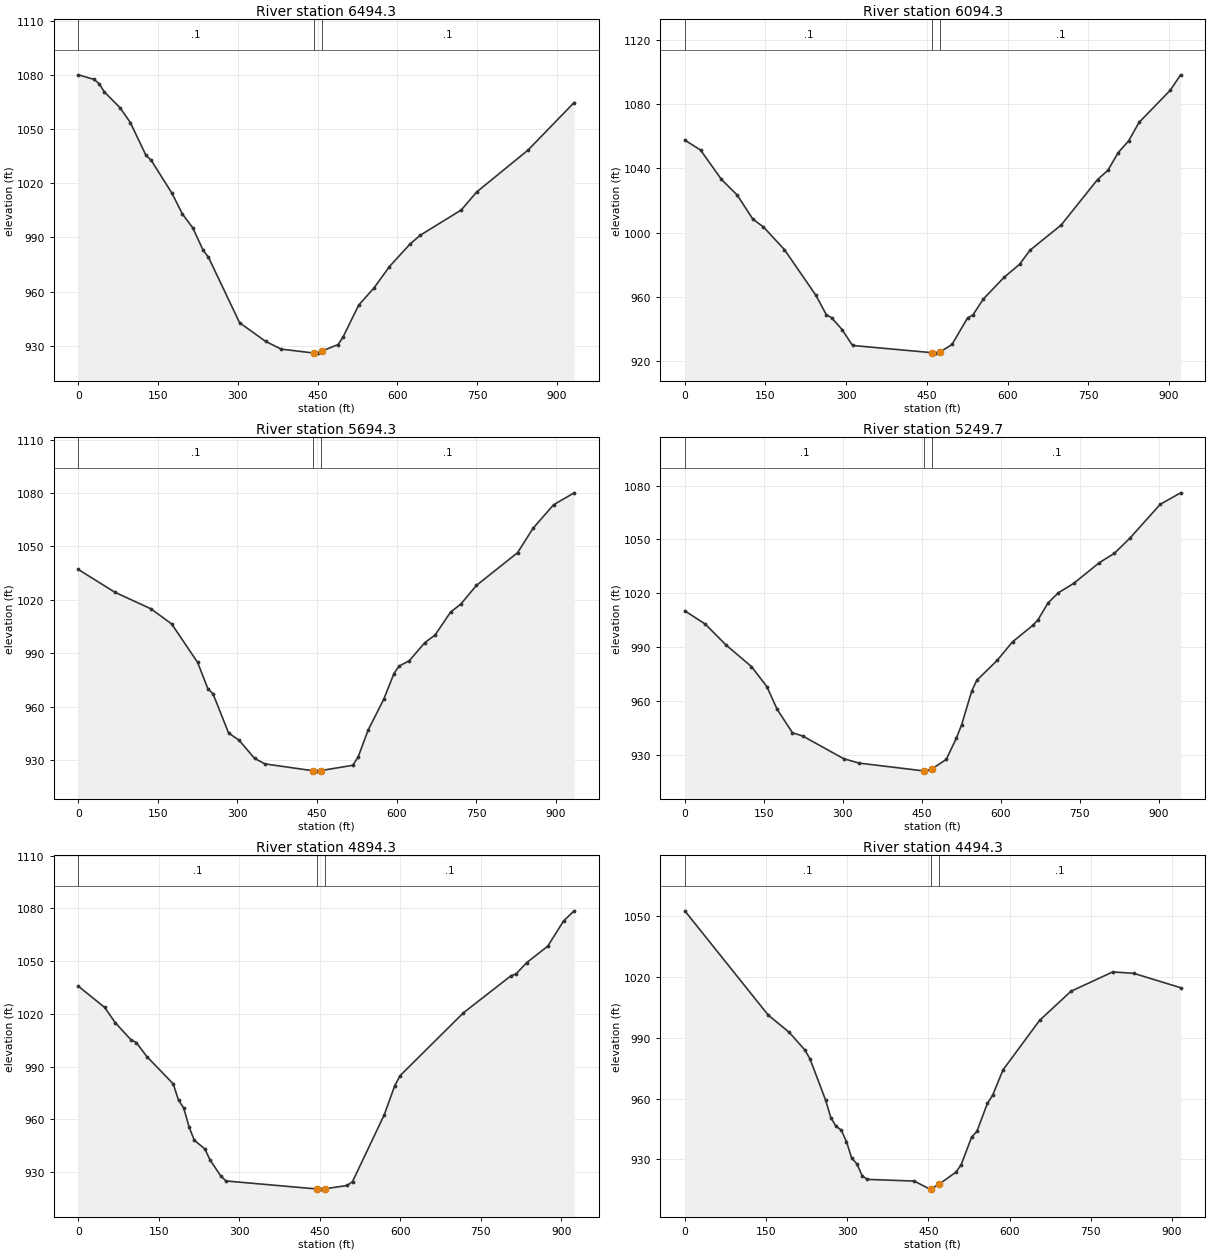
Type RM Length L Ch R = 1 ,6494.3,390.05,400,412.643
XS GIS Cut Line= 3
     1786466.237      386970.915     1786100.431      386708.783
     1785735.801      386392.663
#Sta/Elev= 30
       0 1079.96    29.3 1077.45    39.1 1075.08    48.9 1070.50    78.3 1061.81
    97.8 1053.57   127.2 1035.44   137.0 1032.72   176.1 1014.46   195.7 1002.98
   215.2  995.32   234.8  982.89   244.6  979.12   303.3  942.81   352.2  932.51
   381.5  928.22   442.5  926.05   450.0  925.99   457.5  927.08   488.6  930.73
   498.3  935.14   527.2  952.51   556.2  962.08   585.2  973.89   623.8  986.32
   643.1  991.21   720.3 1005.20   749.2 1015.14   845.7 1038.28   932.6 1064.64
#Mann= 3 , 0 , 0
       0     0.1       0   442.5   0.045       0   457.5     0.1       0
Bank Sta=   442.5,   457.5
Exp/Cntr=0.3,0.1

Type RM Length L Ch R = 1 ,6094.3,396.561,400,390.564
XS GIS Cut Line= 3
     1786573.790      386853.201     1786349.181      386442.900
     1786215.649      386009.040
#Sta/Elev= 30
       0 1057.52    29.2 1051.35    68.2 1033.03    97.4 1023.36   126.7 1008.28
   146.2 1003.53   185.2  989.44   243.6  961.05   263.1  948.96   272.9  947.08
   292.3  939.74   311.8  929.83   460.3  925.33   467.8  925.07   475.3  925.93
   496.7  930.47   525.7  947.01   535.4  948.70   554.7  958.61   593.3  972.13
   622.3  980.28   641.6  989.03   699.6 1004.70   767.2 1032.97   786.5 1038.71
   805.8 1049.79   825.1 1057.06   844.4 1068.51   902.4 1088.49   921.7 1098.09
#Mann= 3 , 0 , 0
       0     0.1       0   460.3   0.045       0   475.3     0.1       0
Bank Sta=   460.3,   475.3
Exp/Cntr=0.3,0.1

Type RM Length L Ch R = 1 ,5694.3,468.414,444.626,428.936
XS GIS Cut Line= 3
     1786860.342      386693.317     1786702.040      386272.720
     1786391.957      385899.375
#Sta/Elev= 30
       0 1037.05    68.4 1024.34   136.8 1014.96   175.9 1006.48   224.7  984.96
   244.2  970.13   254.0  967.18   283.3  945.20   302.9  941.23   332.2  931.00
   351.7  927.90   441.9  924.07   449.4  923.83   456.9  924.12   517.3  927.11
   527.1  931.53   546.5  947.03   575.6  964.07   595.0  978.63   604.7  982.79
   624.1  985.86   653.2  995.97   672.6 1000.27   701.8 1013.13   721.2 1017.65
   750.3 1028.06   828.0 1046.46   857.1 1060.13   895.9 1073.37   934.7 1080.07
#Mann= 3 , 0 , 0
       0     0.1       0   441.9   0.045       0   456.9     0.1       0
Bank Sta=   441.9,   456.9
Exp/Cntr=0.3,0.1

Type RM Length L Ch R = 1 ,5249.7,355.598,355.374,354.876
XS GIS Cut Line= 3
     1787411.401      386040.953     1786909.531      385973.651
     1786526.773      385766.076
#Sta/Elev= 30
       0 1010.26    39.0 1002.80    77.9  991.32   126.6  979.17   155.8  968.07
   175.3  955.42   204.5  942.28   224.0  940.48   301.9  927.83   331.1  925.39
   455.3  920.99   457.7  920.92   470.3  922.35   496.6  927.42   516.0  939.42
   525.7  946.69   545.1  965.61   554.7  971.55   593.4  982.64   622.5  992.95
   661.2 1002.18   670.9 1005.29   690.2 1014.73   709.6 1020.30   738.6 1025.50
   787.0 1036.98   816.0 1042.30   845.0 1050.58   903.1 1069.59   941.8 1075.98
#Mann= 3 , 0 , 0
       0     0.1       0   455.3   0.045       0   470.3     0.1       0
Bank Sta=   455.3,   470.3
Exp/Cntr=0.3,0.1

Type RM Length L Ch R = 1 ,4894.3,408.841,400,391.529
XS GIS Cut Line= 3
     1787514.796      385724.918     1787068.549      385653.179
     1786601.527      385583.902
#Sta/Elev= 30
       0 1035.72    49.1 1023.62    68.8 1014.95    98.3 1005.15   108.1 1003.65
   127.7  995.67   176.9  980.15   186.7  970.87   196.5  966.36   206.3  955.71
   216.2  948.05   235.8  943.12   245.6  936.83   265.3  927.82   275.1  924.91
   444.5  920.35   452.0  920.26   459.5  920.45   501.2  922.34   511.0  924.55
   570.0  962.44   589.7  979.07   599.5  984.76   717.6 1020.54   806.1 1041.57
   815.9 1042.73   835.6 1049.10   874.9 1058.49   904.4 1072.83   924.1 1078.59
#Mann= 3 , 0 , 0
       0     0.1       0   444.5   0.045       0   459.5     0.1       0
Bank Sta=   444.5,   459.5
Exp/Cntr=0.3,0.1

Type RM Length L Ch R = 1 ,4494.3,409.449,400,393.095
XS GIS Cut Line= 3
     1787441.584      385162.955     1786991.640      385269.910
     1786549.878      385372.914
#Sta/Elev= 30
       0 1052.51   154.2 1001.10   192.7  992.69   221.6  983.98   231.2  979.61
   260.1  959.28   269.8  950.56   279.4  946.29   289.1  944.43   298.7  938.75
   308.3  930.64   318.0  927.77   327.6  921.94   337.2  920.13   423.9  919.31
   452.8  915.33     455  915.48     470  917.78   501.1  923.73   510.7  927.42
   530.0  941.02   539.7  943.78   559.0  957.57   568.6  961.51   587.9  974.09
   655.5  998.51   713.4 1012.84   790.6 1022.39   829.2 1021.71   916.1 1014.62
#Mann= 3 , 0 , 0
       0     0.1       0     455   0.045       0     470     0.1       0
Bank Sta=     455,     470
Exp/Cntr=0.3,0.1

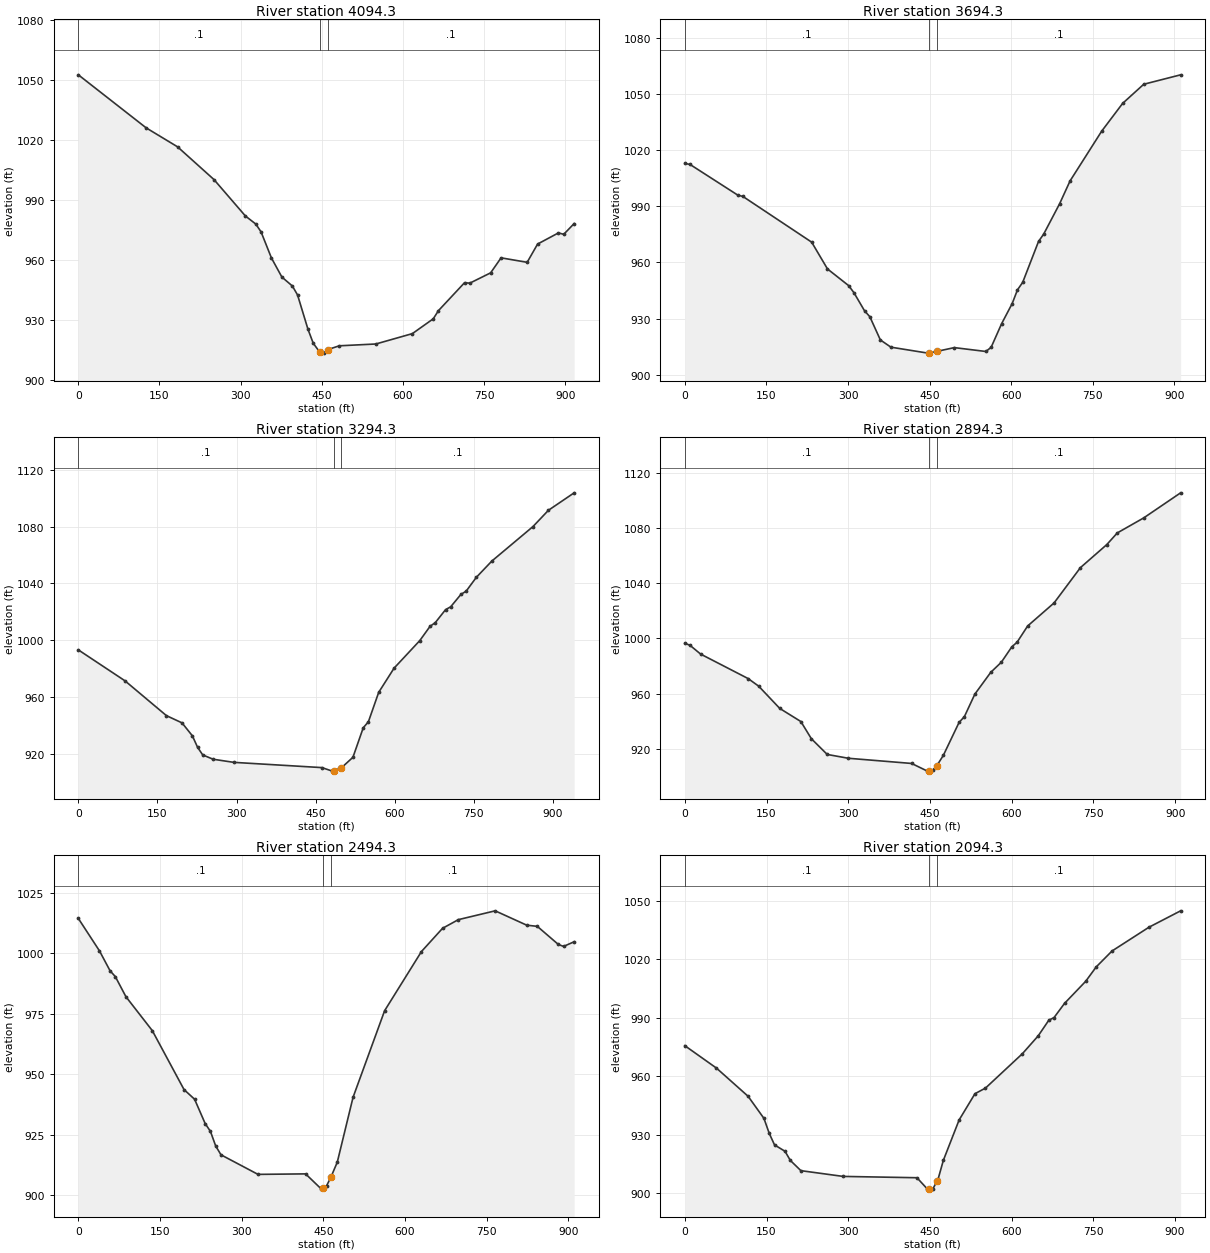
Type RM Length L Ch R = 1 ,4094.3,393.763,400,404.564
XS GIS Cut Line= 3
     1787265.532      384618.864     1786904.375      384893.259
     1786505.489      385128.509
#Sta/Elev= 30
       0 1052.43   125.5 1025.93   183.4 1016.49   250.9 1000.10   308.8  981.97
   328.1  977.92   337.8  974.03   357.1  960.94   376.4  951.43   395.7  946.99
   405.3  942.52   424.6  925.36   434.3  918.41   446.1  914.05   453.6  913.47
   461.1  915.23   482.5  917.13   550.0  918.03   617.6  923.21   656.2  930.61
   665.8  934.68   714.1  948.65   723.7  948.40   762.3  953.56   781.6  961.05
   829.8  958.81   849.1  967.93   887.7  973.51   897.4  972.79   916.7  978.18
#Mann= 3 , 0 , 0
       0     0.1       0   446.1   0.045       0   461.1     0.1       0
Bank Sta=   446.1,   461.1
Exp/Cntr=0.3,0.1

Type RM Length L Ch R = 1 ,3694.3,393.412,400,414.179
XS GIS Cut Line= 3
     1787102.857      384404.478     1786677.677      384571.102
     1786247.579      384718.662
#Sta/Elev= 30
       0 1012.95     9.7 1012.38    97.2  996.03   106.9  995.27   233.2  970.85
   262.3  956.52   301.2  947.61   310.9  943.83   330.4  934.14   340.1  931.00
   359.5  918.56   378.9  914.70   446.9  911.52   449.2  911.59   464.2  912.51
   495.4  914.47   553.4  912.40   563.1  914.64   582.4  927.28   601.8  938.03
   611.5  945.35   621.1  949.36   650.2  971.22   659.8  975.21   688.9  991.34
   708.2 1003.61   766.3 1030.19   804.9 1045.07   843.6 1055.27   911.4 1060.31
#Mann= 3 , 0 , 0
       0     0.1       0   449.2   0.045       0   464.2     0.1       0
Bank Sta=   449.2,   464.2
Exp/Cntr=0.3,0.1

Type RM Length L Ch R = 1 ,3294.3,389.079,400,402.362
XS GIS Cut Line= 3
     1787031.306      384175.912     1786540.543      384203.290
     1786111.104      384073.021
#Sta/Elev= 30
       0  993.11    88.5  971.30   167.1  946.76   196.6  941.68   216.3  932.53
   226.1  924.48   235.9  919.08   255.6  916.04   294.9  913.84   462.0  910.14
   481.7  907.66     484  907.79     499  910.02   520.8  917.43   540.3  938.20
   550.1  942.46   569.6  963.17   598.8  980.23   647.6  999.68   667.1 1009.74
   676.9 1012.30   696.4 1021.45   706.2 1023.49   725.7 1032.27   735.4 1034.45
   754.9 1044.28   784.2 1055.70   862.2 1080.01   891.5 1091.49   940.3 1103.79
#Mann= 3 , 0 , 0
       0     0.1       0     484   0.045       0     499     0.1       0
Bank Sta=     484,     499
Exp/Cntr=0.3,0.1

Type RM Length L Ch R = 1 ,2894.3,398.582,400,400.575
XS GIS Cut Line= 3
     1787072.398      384012.757     1786653.592      383834.919
     1786234.786      383657.081
#Sta/Elev= 30
       0  996.57     9.7  994.98    29.0  988.68   116.2  970.94   135.5  965.47
   174.3  949.30   213.0  939.82   232.3  927.36   261.4  915.97   300.1  913.21
   416.3  909.45   445.3  903.89   447.5  904.05   455.0  904.61   462.5  907.80
   474.4  915.23   503.4  939.19   513.1  943.32   532.4  959.70   561.5  975.43
   580.9  982.74   600.2  993.93   609.9  997.29   629.3 1009.05   677.7 1025.70
   726.1 1051.28   774.5 1067.98   793.8 1076.43   842.2 1087.29   910.0 1105.47
#Mann= 3 , 0 , 0
       0     0.1       0   447.5   0.045       0   462.5     0.1       0
Bank Sta=   447.5,   462.5
Exp/Cntr=0.3,0.1

Type RM Length L Ch R = 1 ,2494.3,405.275,400,394.998
XS GIS Cut Line= 3
     1787241.774      383684.145     1786833.855      383479.615
     1786420.202      383291.195
#Sta/Elev= 30
       0 1014.49    38.8 1001.09    58.3  992.84    68.0  990.42    87.4  982.13
   135.9  968.08   194.2  943.69   213.6  939.70   233.0  929.65   242.7  926.41
   252.4  920.34   262.1  916.71   330.1  908.62   417.5  908.83   446.6  902.52
   448.8  902.86   456.3  904.00   463.8  907.37   475.7  913.65   504.7  940.50
   562.7  976.33   630.4 1000.81   669.1 1010.40   698.1 1013.99   765.8 1017.64
   823.8 1011.70   843.2 1011.22   881.9 1003.72   891.5 1002.92   910.9 1004.85
#Mann= 3 , 0 , 0
       0     0.1       0   448.8   0.045       0   463.8     0.1       0
Bank Sta=   448.8,   463.8
Exp/Cntr=0.3,0.1

Type RM Length L Ch R = 1 ,2094.3,424.39,429.321,434.821
XS GIS Cut Line= 3
     1787439.697      383223.306     1786996.557      383119.156
     1786551.171      383026.301
#Sta/Elev= 30
       0  975.60    58.1  964.10   116.2  949.65   145.3  938.31   155.0  930.64
   164.7  924.73   184.0  921.44   193.7  916.78   213.1  911.52   290.6  908.57
   426.2  907.89   445.5  902.05   447.7  902.06   455.2  902.08   462.7  905.97
   464.9  907.11   474.6  916.78   503.6  937.53   532.7  950.98   552.0  953.85
   619.8  971.49   648.8  980.64   668.2  988.63   677.9  990.02   697.2  997.31
   735.9 1008.58   755.3 1015.98   784.3 1024.13   852.1 1036.32   910.2 1044.72
#Mann= 3 , 0 , 0
       0     0.1       0   447.7   0.045       0   462.7     0.1       0
Bank Sta=   447.7,   462.7
Exp/Cntr=0.3,0.1

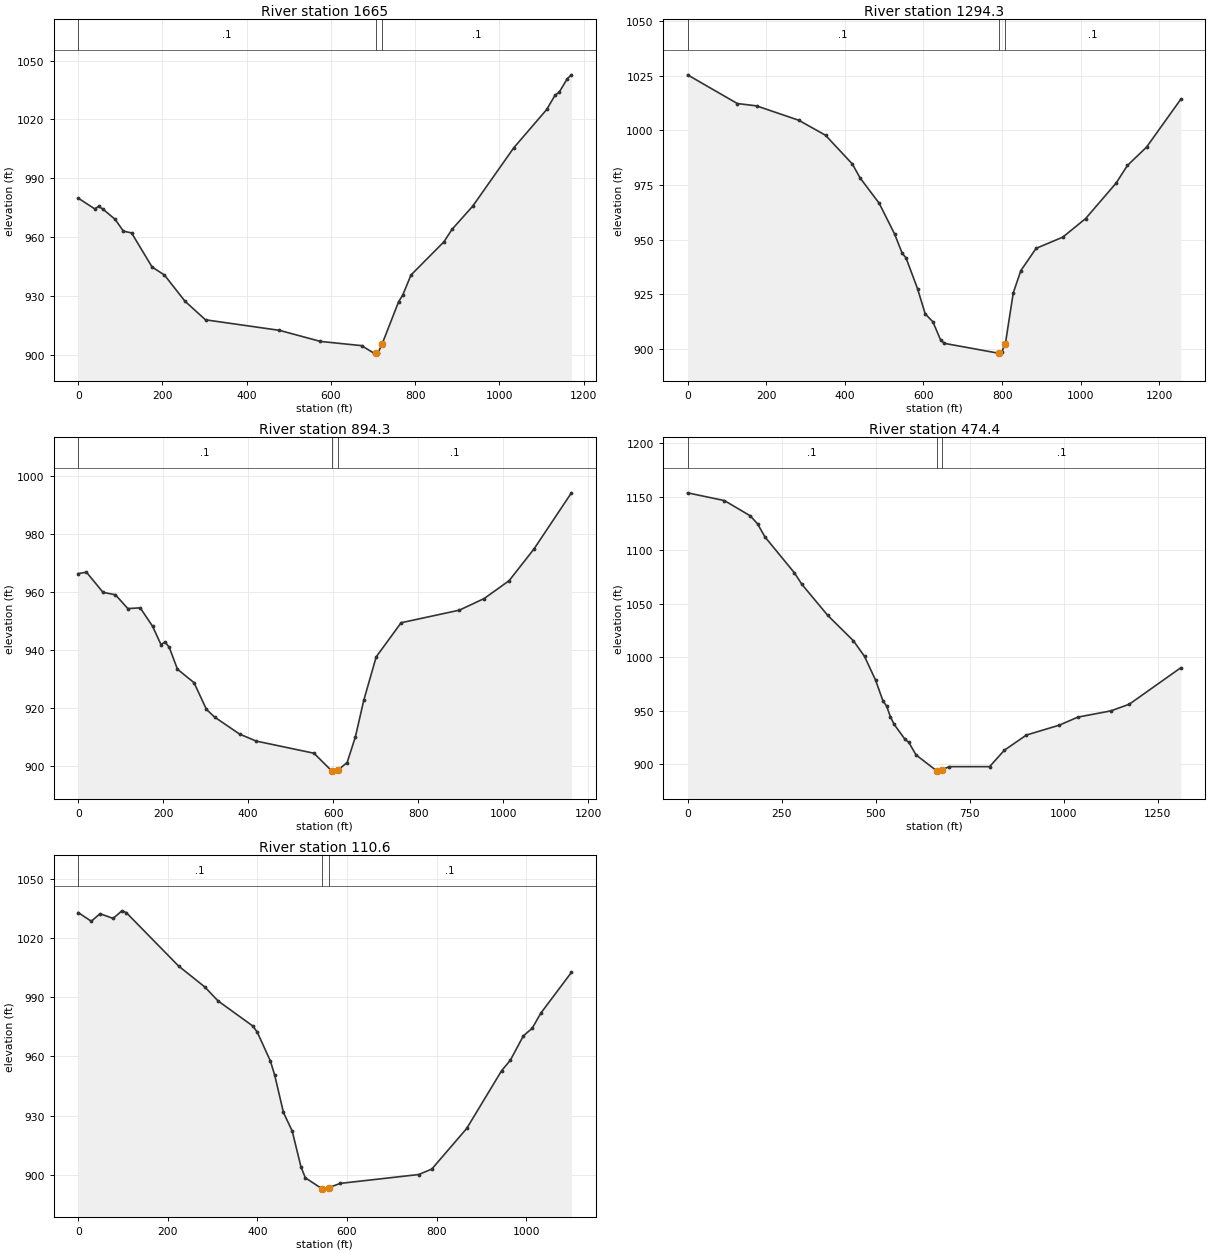
Type RM Length L Ch R = 1 ,1665,369.252,370.679,373.4
XS GIS Cut Line= 3
     1787793.877      383129.593     1787247.352      382772.030
     1786780.574      382548.032
#Sta/Elev= 30
       0  979.95    39.0  974.52    48.7  975.72    58.5  974.37    87.7  969.14
   107.2  963.14   126.7  962.23   175.5  944.83   204.7  940.80   253.4  927.46
   302.2  917.97   477.6  912.61   575.1  906.96   672.6  904.81   701.9  901.00
     706  901.06   711.7  901.14     721  905.43   760.6  927.17   770.3  930.53
   789.9  940.78   868.0  957.66   887.5  964.08   936.4  975.83  1034.1 1005.63
  1112.2 1025.10  1131.8 1032.33  1141.5 1033.80  1161.1 1040.81  1170.8 1042.75
#Mann= 3 , 0 , 0
       0     0.1       0     706   0.045       0     721     0.1       0
Bank Sta=     706,     721
Exp/Cntr=0.3,0.1

Type RM Length L Ch R = 1 ,1294.3,396.281,400,387.484
XS GIS Cut Line= 3
     1788050.727      382804.249     1787353.352      382413.274
     1786969.894      382168.355
#Sta/Elev= 30
       0 1025.36   126.7 1012.24   175.5 1011.17   282.7 1004.61   351.0  997.74
   419.2  984.60   438.7  978.29   487.5  966.64   526.5  952.66   546.0  943.79
   555.7  941.70   585.0  927.61   604.5  916.11   624.0  912.48   643.5  904.26
   653.2  902.62   789.7  898.15     792  898.25   799.5  898.58     807  902.27
   809.2  903.35   828.5  925.71   847.9  935.91   886.6  946.04   954.4  951.16
  1012.5  959.65  1089.9  975.84  1119.0  983.97  1167.4  992.29  1254.5 1014.19
#Mann= 3 , 0 , 0
       0     0.1       0     792   0.045       0     807     0.1       0
Bank Sta=     792,     807
Exp/Cntr=0.3,0.1

Type RM Length L Ch R = 1 ,894.3,444.508,419.92,410.273
XS GIS Cut Line= 3
     1788050.727      382461.782     1787578.536      382085.865
     1787021.748      382065.864
#Sta/Elev= 30
       0  966.38    19.5  966.85    58.4  959.90    87.6  959.06   116.8  954.29
   146.0  954.54   175.2  948.14   194.7  941.88   204.4  942.73   214.2  940.93
   233.6  933.35   272.6  928.70   301.8  919.47   321.2  916.80   379.7  910.95
   418.6  908.54   554.9  904.33   596.1  898.30   603.6  898.15   611.1  898.51
   632.9  901.12   652.4  910.03   672.0  922.60   701.3  937.62   759.9  949.40
   896.8  953.74   955.4  957.76  1014.1  963.93  1072.7  974.90  1160.7  994.27
#Mann= 3 , 0 , 0
       0     0.1       0   596.1   0.045       0   611.1     0.1       0
Bank Sta=   596.1,   611.1
Exp/Cntr=0.3,0.1

Type RM Length L Ch R = 1 ,474.4,374.195,363.79,353.386
XS GIS Cut Line= 3
     1788266.568      381731.645     1787711.039      381672.726
     1787021.292      381973.142
#Sta/Elev= 30
       0 1153.74    98.0 1146.49   166.6 1132.26   186.2 1124.71   205.8 1112.50
   284.2 1078.90   303.8 1068.27   372.4 1039.28   441.0 1015.40   470.4 1000.89
   499.8  978.63   519.4  959.31   529.2  954.41   539.0  944.61   548.8  937.48
   578.2  923.27   588.0  920.51   607.5  908.69     662  893.96   666.1  893.58
     677  894.94   695.4  897.77   802.9  897.77   842.0  913.08   900.6  927.29
   988.5  936.59  1037.4  944.06  1125.3  949.91  1174.2  956.14  1311.0  990.20
#Mann= 3 , 0 , 0
       0     0.1       0     662   0.045       0     677     0.1       0
Bank Sta=     662,     677
Exp/Cntr=0.3,0.1

Type RM Length L Ch R = 1 ,110.6,121.735,110.615,99.495
XS GIS Cut Line= 3
     1787674.013      381074.790     1787297.257      381547.429
     1786950.278      381902.736
#Sta/Elev= 30
       0 1032.83    29.2 1028.43    48.7 1032.24    78.0 1029.86    97.5 1033.70
   107.2 1032.83   224.2 1005.76   282.7  995.18   312.0  988.15   390.0  975.39
   399.7  972.36   428.9  957.79   438.7  950.56   458.2  931.67   477.7  922.33
   497.2  904.29   506.9  898.66   544.1  893.11   545.9  892.89   559.1  893.62
   584.9  895.79   760.2  900.28   789.4  903.05   867.3  923.58   945.3  952.83
   964.7  958.10   993.9  970.47  1013.4  974.25  1032.9  981.96  1101.1 1002.56
#Mann= 3 , 0 , 0
       0     0.1       0   544.1   0.045       0   559.1     0.1       0
Bank Sta=   544.1,   559.1
Exp/Cntr=0.3,0.1